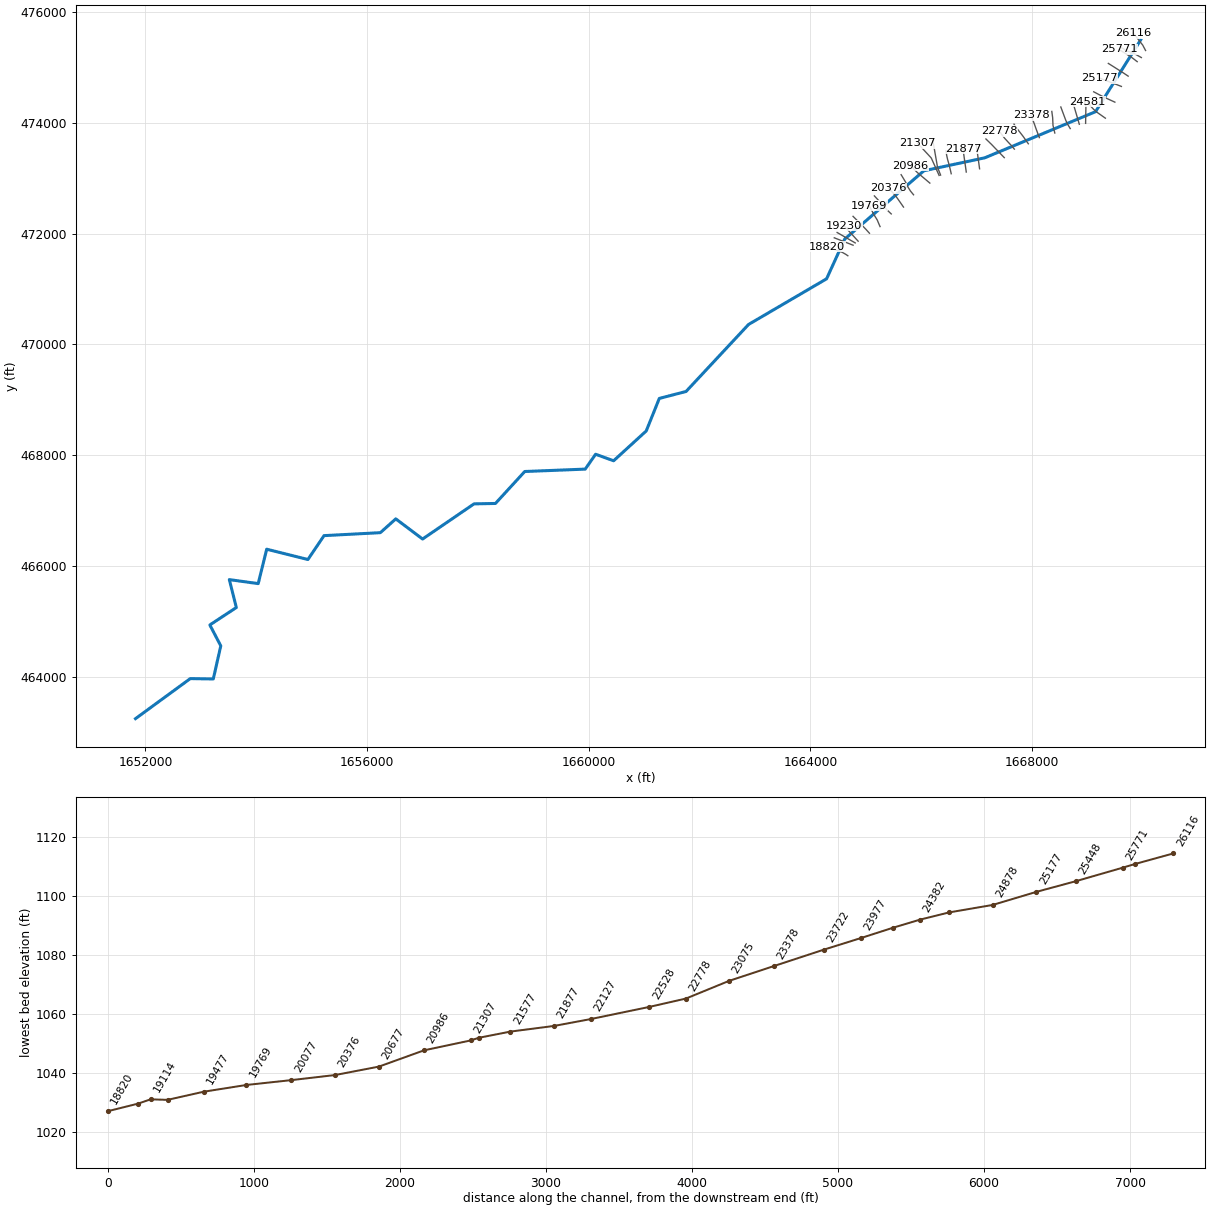
--- BigRnI.prj (project) ---

Proj Title=BigRnI
Current Plan=p01
Default Exp/Contr=0,0
English Units
Geom File=g01
Flow File=f01
Plan File=p01
BEGIN DESCRIPTION:
---------- MODELED AS PART OF WVEM CTP PROGRAM, 2025----------
Stream Name: Big Run I
Flood Zone: AFH
Marshall County, WV
HEC-RAS Version: RAS 6.6
Vertical Datum: NAVD88
Projection: NAD 1983 StatePlane West Virginia N FIPS 4701 (US Feet)
Terrain: 1-meter West Virginia FEMA R3 South Central (collected 2018-2019)
Land Use: 2024 NLCD
Hydrologic Method:
Duda et al., "Estimation of magnitude and frequency of floods for rural, unregulated streams in and near Virginia and West Virginia." September 8, 2025.
Additional Model Notes:
None
END DESCRIPTION:
DSS Export Rating Curves= 0
DSS Export Rating Curve Sorted= 0
DSS Export Volume Flow Curves= 0
DXF OffsetX= 0
DXF OffsetY= 0
DXF ScaleX= 0
DXF ScaleY= 0

--- BigRnI.p01 (plan) ---

Plan Title=Floodplain
Program Version=6.60
Short Identifier=Floodplain
Geom File=g01
Flow File=f01
Subcritical Flow
K Sum by GR= 0
Std Step Tol= 0.01
Critical Tol= 0.01
Num of Std Step Trials= 20
Max Error Tol= 0.3
Flow Tol Ratio= 0.001
Split Flow NTrial= 30
Split Flow Tol= 0.02
Split Flow Ratio= 0.02
Log Output Level= 0
Friction Slope Method= 1
Unsteady Friction Slope Method= 2
Unsteady Bridges Friction Slope Method= 1
Parabolic Critical Depth
Global Vel Dist= 0 , 0 , 0
Global Log Level= 0
CheckData=False
Encroach Param=-1 ,0,0, 0
Flow Ratio Tolerance=0.1
Flow Ratio Min Ratio=0.5
Flow Ratio Max Ratio=4
Flow Ratio Max Iterations= 10
Mapping Interval=1HOUR
Computation Time Step Use Courant=        0
Computation Time Step Use Time Series=    0
Computation Time Step Count To Double=0
Computation Time Step Max Doubling=0
Computation Time Step Max Halving=0
Computation Time Step Residence Courant=0
Run HTab= 0
Run UNet= 0
Run Sediment= 0
Run PostProcess= 0
Run WQNet= 0
Run RASMapper=-1
UNET Theta= 0
UNET Theta Warmup= 0
UNET ZTol= 0
UNET ZSATol= 0
UNET MxIter= 0
UNET Max Iter WO Improvement= 0
UNET MaxInSteps= 0
UNET DtIC= 0
UNET DtMin= 0
UNET MaxCRTS= 0
UNET WFStab= 0
UNET SFStab= 0
UNET WFX= 1
UNET SFX= 1
UNET Gravity=32.17405
UNET 1D Methodology=Finite Difference
UNET DSS MLevel= 1
UNET Pardiso=0
UNET DZMax Abort= 0
UNET Use Existing IB Tables= 0
UNET Froude Reduction=False
UNET Froude Limit= 0
UNET Froude Power= 0
UNET D1 Cores= 0
UNET WindReference=Eulerian
UNET WindDragFormulation=Hsu (1988)
UNET D2 Coriolis=0
UNET D2 Cores= 0
UNET D2 Theta= 1
UNET D2 Theta Warmup= 1
UNET D2 Z Tol= 0.01
UNET D2 Volume Tol= 0.01
UNET D2 Max Iterations= 20
UNET D2 Advanced Convergence=0
UNET D2 WS Max Tol=0.15
UNET D2 WS RMS Tol=0.002
UNET D2 WS Stall Tol=1
UNET D2 Equation= 0
UNET D2 RampUpFraction=0.1
UNET D2 TimeSlices= 1
UNET D2 Turbulence Formulation=Non-Conservative (original)
UNET D2 Eddy Viscosity=0.3
UNET D2 Transverse Eddy Viscosity=0.1
UNET D2 Smagorinsky Mixing=0
UNET D2 BCVolumeCheck=0
UNET D2 Cores=0
UNET D2 SolverType=PARDISO (Direct)
UNET D2 Minimum Iterations= 3
UNET D2 Maximum Iterations= 30
UNET D2 Restart Number= 10
UNET D2 Relaxation Coeff=1.3
UNET D2 SOR Precondition Iterations= 10
UNET D2 ILUT Maximum Fill= 8
UNET D2 ILUT Tolerance=1E-08
UNET D2 Convergence Tolerance=0.00001
PS Theta= 1
PS WS Tol= 0.01
PS Volume Tol= 0.01
PS Max Iterations= 20
PS Equation= 0
PS Advance Time Step=-1
PS Target Courant=0.9
PS Time Slices= 1
PS Iterate With 2D=0
PS Project Initial WSE from DS=-1
PS Ramp Up Initial WSE from US=-1
PS Cores=0
UNET D1D2 MaxIter= 0
UNET D1D2 ZTol=0.01
UNET D1D2 QTol=0.1
UNET D1D2 MinQTol=1
Write IC File= 0
Write IC File at Fixed DateTime=0
Write IC File at Sim End=0
Echo Input=False
Echo Parameters=False
Echo Output=False
Write Detailed= 0
HDF Write Warmup=0
HDF Write Time Slices=0
HDF Flush=0
HDF Compression= 1
HDF Chunk Size= 1
HDF Spatial Parts= 1
HDF Use Max Rows=0
HDF Fixed Rows= 1
Calibration Method= 0
Calibration Iterations= 20
Calibration Max Change=0.05
Calibration Tolerance=0.2
Calibration Maximum=1.5
Calibration Minimum=0.5
Calibration Optimization Method= 1
WQ AD Non Conservative
WQ ULTIMATE=-1
WQ Max Comp Step=1HOUR
WQ Output Interval=15MIN
WQ Output Selected Increments= 0
WQ Create Restart=0
WQ Fixed Restart=0
WQ System Summary=0
WQ Write To DSS=0
Sorting and Armoring Iterations= 10
XS Update Threshold= 0.02
Bed Roughness Predictor= 0
Processes Affected by Predictor=Sediment Only
Hydraulics Update Threshold= 0.02
Energy Slope Method= 1
Volume Change Method= 1
Sediment Retention Method= 0
Sediment TS Multiplier= 1
Warm Up Method= 0
XS Weighting Method= 0
Number of US Weighted Cross Sections= 1
Number of DS Weighted Cross Sections= 1
Upstream XS Weight=0
Main XS Weight=1
Downstream XS Weight=0
Number of DS XS's Weighted with US Boundary= 1
Upstream Boundary Weight= 1
Weight of XSs Associated with US Boundary= 0
Number of US XS's Weighted with DS Boundary= 1
Downstream Boundary Weight= 0.5
Weight of XSs Associated with DS Boundary= 0.5
Percentile Method= 0
Sediment Output Level= 3
Mass or Volume Output= 0
Output Increment Type= 1
Profile and TS Output Increment= 1
Transport Output Increment 1
XS Output Flag= 0
XS Output Increment= 10
Read HDF5 Sediment Hotstart= 0
Sediment Hotstart Type= 0
Write Gradation File= 0
Read Gradation Hotstart= 0
Write HDF5 File= 1
Write Binary Output= 1
Write DSS Sediment File= 0
DSS Sediment Output Type= 1
SV Curve= 0
Specific Gage Flag= 0
Subcell Erosion Methods= 0
Subcell Deposition Methods= 0
Advection Scheme= 1
Matrix Solver= 0
Implicit Weighting Factor= 1
Maximum Outer Loop Convergence Iterations= 5
Convergence Maximum Absolute= 0.001
Convergence RMSE= 0.0001
Grain Fractions Max Abs Error= 0.001
Max Subgrid Regions= 1
Max Subgrid Length Scale= 3.402823E+38
Initial Layer Thickness= 3
Min Layer Thickness= 0.1
Max Layer Thickness= 6
Number of Layers= 5

--- BigRnI.f01 (steady flow) ---

Flow Title=Flow
Program Version=6.60
Number of Profiles= 1
Profile Names=P100yr
River Rch & RM=BigRnI,Main,26116
     757
River Rch & RM=BigRnI,Main,23378
     856
River Rch & RM=BigRnI,Main,20986
    1100
River Rch & RM=BigRnI,Main,20077
    1230
River Rch & RM=BigRnI,Main,16984
    1370
River Rch & RM=BigRnI,Main,14079
    1530
River Rch & RM=BigRnI,Main,8623
    1720
Boundary for River Rch & Prof#=BigRnI,Main            , 1
Up Type= 0
Dn Type= 3
Dn Slope=0.015553
DSS Import GetInterval= 0
DSS Import GetPeak= 0
DSS Import FillOption= 0

--- BigRnI.g01 (geometry) ---

Geom Title=Geometry
Program Version=6.60

River Reach=BigRnI          ,Main
Reach XY= 30
     1669961.111      475495.556     1669146.311      474199.467
      1667146.42      473366.819        1666048.      473133.056
     1664619.378      471899.733     1664292.222      471183.333
     1662884.267      470359.467     1661755.799      469149.689
     1661273.422      469024.711     1661037.511      468437.333
      1660448.75      467899.375      1660123.75      468016.875
      1659936.25       467748.75        1658845.      467705.625
     1658316.089      467128.889     1657929.956      467121.778
     1657000.896       466487.05     1656517.872      466850.955
     1656238.737      466601.756     1655222.677      466548.306
     1654931.358466117.382015715     1654187.703      466303.204
     1654034.331      465682.331     1653512.925      465754.643
      1653639.81      465250.643     1653161.482      464936.296
     1653359.012      464559.012     1653223.758      463961.481
     1652808.777      463968.067     1651820.036       463245.51

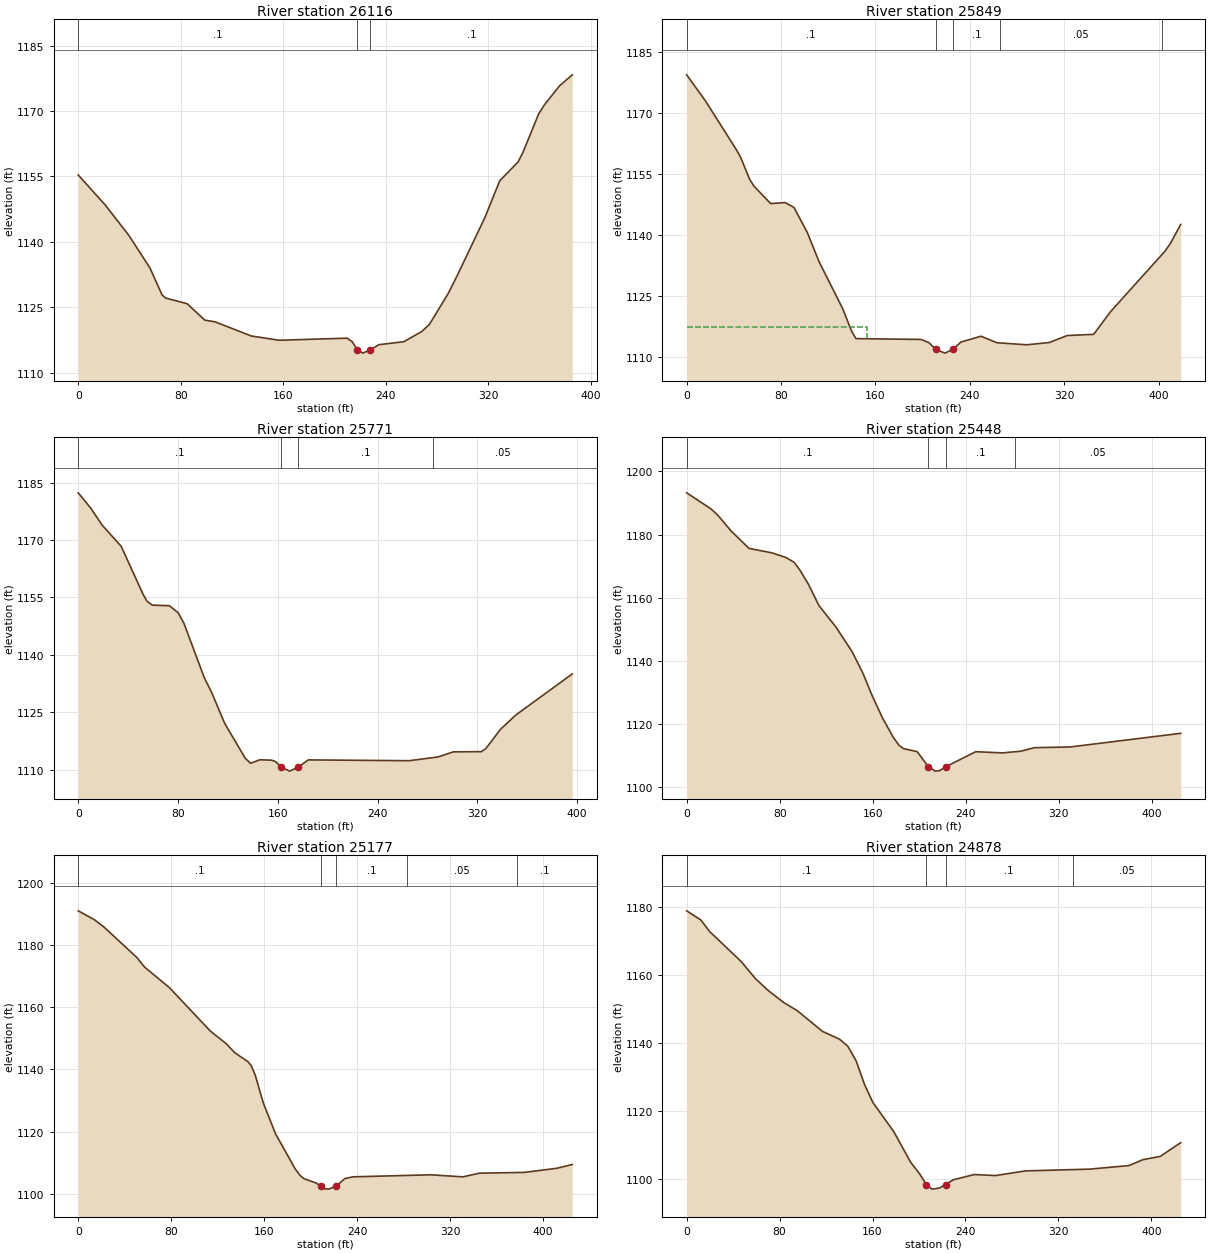
Type RM Length L Ch R = 1 ,26116   ,263.1,266.5,270.6
XS GIS Cut Line= 3
1670049.39225188 475303.643767261669997.81109623475401.636070264
1669828.58615981475618.353818042
#Sta/Elev= 30
       0 1155.32    20.9 1148.51    39.5 1141.49    55.9 1134.06    65.4 1127.87
      68 1127.13      85 1125.82    98.8 1122.06   106.9 1121.65   135.1 1118.42
   156.8 1117.44   209.9 1117.92   213.9  1117.1     218 1115.25   222.2 1114.49
  228.16 1115.28   234.7 1116.42   254.3 1117.12     268 1119.41   274.1 1121.05
   288.8 1128.14   296.4 1132.58   317.4 1145.52   329.1 1154.01   343.4 1158.32
   347.1 1160.45   359.5 1169.35   364.1 1171.47   375.8 1175.76   385.7 1178.28
#Mann= 3 ,-1,0
       0      .1       0     218    .045       0  228.16      .1       0
Bank Sta=218,228.16
XS Rating Curve= 0 ,0
Exp/Cntr(USF)=0,0
Exp/Cntr=0.3,0.1

Type RM Length L Ch R = 1 ,25849   ,79.2,77.7,76.6
XS GIS Cut Line= 4
 1669973.3239829475176.5460023991669811.14946477475267.363501234
1669726.83517751475289.5966599371669600.79480316 475362.81059227
#Sta/Elev= 30
       0 1179.34      16 1172.89    42.3 1160.83    45.8    1159    53.3 1153.66
    57.1 1151.93    71.2 1147.66    83.4  1147.9    90.9 1146.72   102.2 1140.57
   112.2 1133.37   132.3 1121.76   139.8 1116.27   143.5 1114.42   198.6 1114.22
   205.4 1113.42  211.171111.784   218.9 1110.85   225.7 1111.77   232.5 1113.58
   249.5 1115.01     263 1113.41   288.4  1112.9   307.4 1113.46   322.6 1115.18
     345 1115.47   359.4 1121.08     405 1135.78     410 1137.81   418.8 1142.52
#Mann= 5 ,-1,0
       0      .1       0  211.17    .045       0   225.7      .1       0
  265.87     .05       0  403.07      .1       0
#XS Ineff= 2 , 0
          153.07 1117.23
Permanent Ineff=
       F       F
Bank Sta=211.17,225.7
XS Rating Curve= 0 ,0
Exp/Cntr(USF)=0,0
Exp/Cntr=0.3,0.1

Type RM Length L Ch R = 1 ,25771   ,324.5,323.7,324.1
XS GIS Cut Line= 4
1669898.22142669475102.4515924631669778.71918751475195.079792436
1669740.72491794475216.3936509781669569.56820901475322.663497582
#Sta/Elev= 30
       0 1182.31     9.9 1178.37    19.3 1173.83    34.4 1168.38      52 1155.83
    55.1 1154.04    59.3 1153.01    73.1 1152.85    80.1 1151.03    84.8 1148.23
   101.1 1134.06   106.9 1130.29   117.4 1122.18   133.9 1113.07   138.2 1111.74
   145.6 1112.65     155 1112.55   158.2 1112.18  162.811110.717   169.5 1109.69
  176.351110.718   184.5 1112.62   265.4 1112.41   288.5 1113.39   300.8 1114.72
   323.3 1114.77     327 1115.62   338.7 1120.62   350.8  1124.3   396.2 1135.06
#Mann= 4 ,-1,0
       0      .1       0  162.81    .045       0  176.35      .1       0
  284.76     .05       0
Bank Sta=162.81,176.35
XS Rating Curve= 0 ,0
Exp/Cntr(USF)=0,0
Exp/Cntr=0.3,0.1

Type RM Length L Ch R = 1 ,25448   ,269.8,270.8,272.3
XS GIS Cut Line= 6
1669735.08877757474841.3505932991669662.41536649474890.147411719
1669599.41582057474930.8510704791669514.82347007474984.181016311
1669451.37904315475024.1786397251669377.36081849475070.842588395
#Sta/Elev= 30
       0 1193.22    20.9 1188.14    26.8 1186.12    38.5 1181.03    53.6 1175.63
    73.3  1174.2    85.4 1172.74    92.5 1171.19    97.2 1168.87   104.8 1164.23
   113.8 1157.49   128.2 1150.81   142.3 1142.92   151.8 1135.93   159.4 1129.11
   168.4 1121.95   177.9 1115.66   182.7 1113.22   186.6 1112.18   198.3 1111.23
  207.871106.491   213.8 1105.06   217.6 1105.21  223.141106.492   248.7 1111.22
   271.9 1110.83   287.5 1111.38   299.1 1112.49   329.8 1112.71     425 1117.04
#Mann= 4 ,-1,0
       0      .1       0  207.87    .045       0  223.14      .1       0
  282.54     .05       0
Bank Sta=207.87,223.14
XS Rating Curve= 0 ,0
Exp/Cntr(USF)=0,0
Exp/Cntr=0.3,0.1

Type RM Length L Ch R = 1 ,25177   ,299.3,299.3,297.6
XS GIS Cut Line= 6
1669612.79942176474655.4909474251669531.22314134474687.150989085
1669461.15864892474713.9114342631669367.56401984474749.125274584
1669297.36796601474775.5356548431669215.47278859474806.348257259
#Sta/Elev= 30
       0 1191.13    13.9 1188.26    22.1 1185.93    50.3 1176.13    57.3 1172.92
    78.4 1166.39   113.6 1152.39   127.6 1148.21   134.6 1145.41   145.9 1142.53
   148.7  1141.3   152.2 1138.24   159.2 1129.21   169.7 1119.28   186.6 1107.97
   190.8 1105.85   194.2  1104.8   204.8 1103.37  208.511102.386   211.8 1101.54
   215.3 1101.43  221.971102.385   229.3 1104.83   236.3 1105.39     303 1106.04
     331 1105.39     345 1106.57   383.6 1106.82   411.6 1108.14     425 1109.36
#Mann= 5 ,-1,0
       0      .1       0  208.51    .045       0  221.97      .1       0
  282.51     .05       0  377.51      .1       0
Bank Sta=208.51,221.97
XS Rating Curve= 0 ,0
Exp/Cntr(USF)=0,0
Exp/Cntr=0.3,0.1

Type RM Length L Ch R = 1 ,24878   ,298.1,296.8,293.8
XS GIS Cut Line= 6
1669495.06770185474371.8195987491669415.57475059474408.386454761
1669347.43807584474439.7292398361669257.18694401474482.819704846
1669190.64278576474517.6244252621669113.18001418474558.638450846
#Sta/Elev= 30
       0 1178.97    12.3 1176.25    19.5 1172.97    47.2 1163.93    59.2    1159
    70.1 1155.52    83.7 1151.92    95.3 1149.53     117 1143.44   131.5 1141.18
   138.7 1139.09   145.9 1134.78   153.1 1127.82   160.3 1122.51   178.2 1113.98
   192.9 1104.85   200.3 1101.63  206.26 1098.32   211.2 1096.99   217.5  1097.3
  222.871098.321   229.4 1099.73   247.6 1101.29   265.8 1100.99   291.7 1102.36
   346.9 1102.88   380.7 1103.93     393 1105.69   407.6 1106.62   425.3 1110.68
#Mann= 4 ,-1,0
       0      .1       0  206.26    .045       0  222.87      .1       0
  332.51     .05       0
Bank Sta=206.26,222.87
XS Rating Curve= 0 ,0
Exp/Cntr(USF)=0,0
Exp/Cntr=0.3,0.1

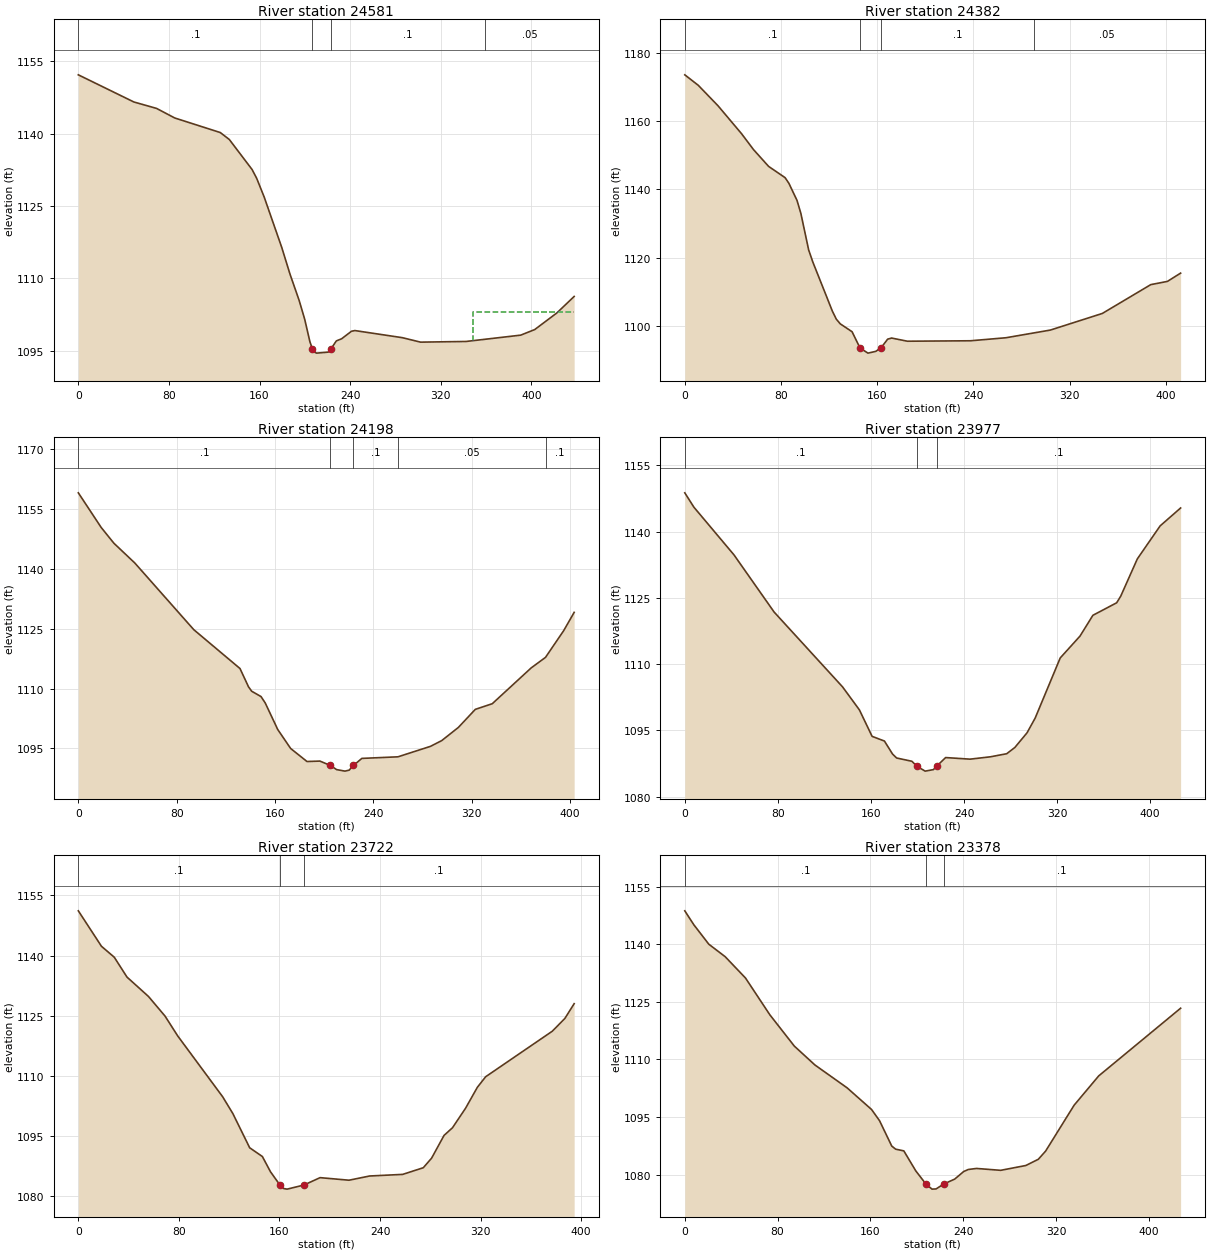
Type RM Length L Ch R = 1 ,24581   ,204.9,199.2,189.6
XS GIS Cut Line= 6
1669323.85774243474082.5147311691669252.32770176474132.910627753
1669191.01680076474176.1070636661669113.81452735474240.154835835
1669061.54757151474296.0566269161669004.78062467474376.539405584
#Sta/Elev= 30
       0 1152.21      49 1146.58    69.1 1145.24    85.1 1143.26   125.3 1140.24
   133.3  1138.8   153.4 1132.57   157.4 1130.78   164.1 1126.86   179.6 1116.41
   186.9 1110.86     195 1105.39   199.9 1101.48   204.5 1096.81  206.661095.375
   208.2  1094.7   210.4 1094.47   220.7 1094.68  223.151095.375   227.8    1097
   232.5 1097.45   241.2 1099.01   244.2 1099.15     286 1097.68   302.2 1096.75
   342.4 1096.89   390.6  1098.2     403 1099.36   422.7 1102.84   437.8 1106.23
#Mann= 4 ,-1,0
       0      .1       0  206.66    .045       0  223.15      .1       0
  359.34     .05       0
#XS Ineff= 2 , 0
                          348.74            1103
Permanent Ineff=
       F       F
Bank Sta=206.66,223.15
XS Rating Curve= 0 ,0
Exp/Cntr(USF)=0,0
Exp/Cntr=0.3,0.1

Type RM Length L Ch R = 1 ,24382   ,178.8,183.9,185
XS GIS Cut Line= 3
1668967.05342901 473988.823253441668972.58398047474292.738481693
1668946.10296666474397.769131156
#Sta/Elev= 30
       0 1173.59    11.2 1170.52    27.6 1164.53    47.3 1156.29    57.1 1151.69
    69.7 1146.75    83.4 1143.45    86.6 1141.77    93.3 1136.79    96.5    1133
     103 1122.26   106.5 1118.69   122.7 1104.34     126 1101.97   129.3  1100.6
   139.1 1098.29   145.7 1093.53   152.3 1092.02   158.8 1092.54   163.21093.588
   168.7 1096.12     172 1096.44   185.1 1095.51   237.6 1095.64   267.1 1096.53
     304 1098.78   347.2 1103.65   387.5  1112.1   401.3 1113.04   412.3 1115.47
#Mann= 4 ,-1,0
       0      .1       0   145.7    .045       0   163.2      .1       0
     290     .05       0
Bank Sta=145.7,163.2
XS Rating Curve= 0 ,0
Exp/Cntr(USF)=0,0
Exp/Cntr=0.3,0.1

Type RM Length L Ch R = 1 ,24198   ,220.1,220.9,221.8
XS GIS Cut Line= 2
1668853.60369905473972.2592781381668740.17690402474359.244814112
#Sta/Elev= 30
       0 1159.09    18.6  1150.4    28.9 1146.46      46 1141.47    93.9 1124.77
   131.5 1115.02   138.4 1110.45     141 1109.33   148.6 1107.99     152  1106.4
   162.2 1099.73   172.7 1094.97     186  1091.7   196.5 1091.81  204.861090.728
   210.1 1089.67   216.9 1089.29   220.3 1089.54   223.8 1090.71   230.6 1092.48
     260 1092.88   286.4  1095.5   295.6 1096.95   309.2 1100.27   322.9 1104.78
   336.7  1106.2   368.4 1115.19     380 1117.82   394.8 1124.53   403.3 1129.11
#Mann= 5 ,-1,0
       0      .1       0  204.86    .045       0   223.8      .1       0
     260     .05       0     380      .1       0
Bank Sta=204.86,223.8
XS Rating Curve= 0 ,0
Exp/Cntr(USF)=0,0
Exp/Cntr=0.3,0.1

Type RM Length L Ch R = 1 ,23977   ,254.3,254.6,248.7
XS GIS Cut Line= 6
  1668689.601465473894.8828885851668643.80431251473970.534640178
  1668611.424456474038.4875882571668576.51343659474132.195734173
1668550.32976192474202.4767615941668519.78192276474284.471348256
#Sta/Elev= 30
       0 1148.76     7.8 1145.52    42.3 1134.71    76.8 1121.77   135.6 1104.84
   150.1 1099.63     161 1093.64   171.6 1092.58   178.6 1089.63   182.1 1088.74
   195.2    1088  199.581086.859   206.6 1085.77   213.7 1086.11   216.41086.858
   224.2 1088.84   245.2 1088.48   262.7 1089.01   276.7 1089.71   283.7 1091.12
   294.2 1094.45   301.2 1097.79   322.7 1111.38   339.7 1116.33   350.8 1121.04
   371.2 1123.87   374.7 1125.36     389 1133.81   408.6 1141.28   426.2 1145.33
#Mann= 3 ,-1,0
       0      .1       0  199.58    .045       0   216.4      .1       0
Bank Sta=199.58,216.4
XS Rating Curve= 0 ,0
Exp/Cntr(USF)=0,0
Exp/Cntr=0.3,0.1

Type RM Length L Ch R = 1 ,23722   ,341.6,344.4,345.9
XS GIS Cut Line= 4
1668410.85252277473814.6973417271668378.40136302473954.177239352
1668372.68487377474090.5788814511668357.28388818474204.189356595
#Sta/Elev= 30
       0 1151.14    18.4 1142.31    28.6 1139.58    38.7 1134.64    55.8 1129.81
      69 1124.91    79.1 1119.96   114.8 1104.83   122.9 1100.65   136.3 1092.12
   146.4 1089.94   152.9 1086.12  160.381082.843   162.8    1082   166.1 1081.82
  179.461082.843   192.3 1084.68   215.3 1084.04   231.7 1085.09     258 1085.49
   274.4 1087.15     281 1089.53   290.9  1095.2   297.6  1097.1     308 1101.96
   317.4 1107.18     324 1109.81     377 1121.15     387 1124.33   394.4 1128.01
#Mann= 3 ,-1,0
       0      .1       0  160.38    .045       0  179.46      .1       0
Bank Sta=160.38,179.46
XS Rating Curve= 0 ,0
Exp/Cntr(USF)=0,0
Exp/Cntr=0.3,0.1

Type RM Length L Ch R = 1 ,23378   ,300,303.4,303.4
XS GIS Cut Line= 6
1668132.70920609 473731.236890421668101.90021259473813.091385499
1668075.48983234473883.2598803341668042.15820609473978.100569919
1668014.95944159474049.067947671  1667982.161935474131.178675845
#Sta/Elev= 30
       0 1148.74     7.8  1145.1    20.7 1140.04    34.8 1136.79    52.3 1131.24
    73.3 1121.65    94.4 1113.49   112.2 1108.56   139.9 1102.61     161 1096.96
   167.9 1094.03   178.4 1087.43   181.8 1086.62   188.8 1086.18   199.1 1080.97
  207.871077.534   213.1 1076.21   216.6 1076.26  223.191077.534   232.7 1078.83
   240.4  1080.8   244.4 1081.33   251.4  1081.6   272.3 1081.11     294 1082.37
   304.7 1083.98     311 1086.11   335.6 1098.08   356.8 1105.72   427.4 1123.36
#Mann= 3 ,-1,0
       0      .1       0  207.87    .045       0  223.19      .1       0
Bank Sta=207.87,223.19
XS Rating Curve= 0 ,0
Exp/Cntr(USF)=0,0
Exp/Cntr=0.3,0.1

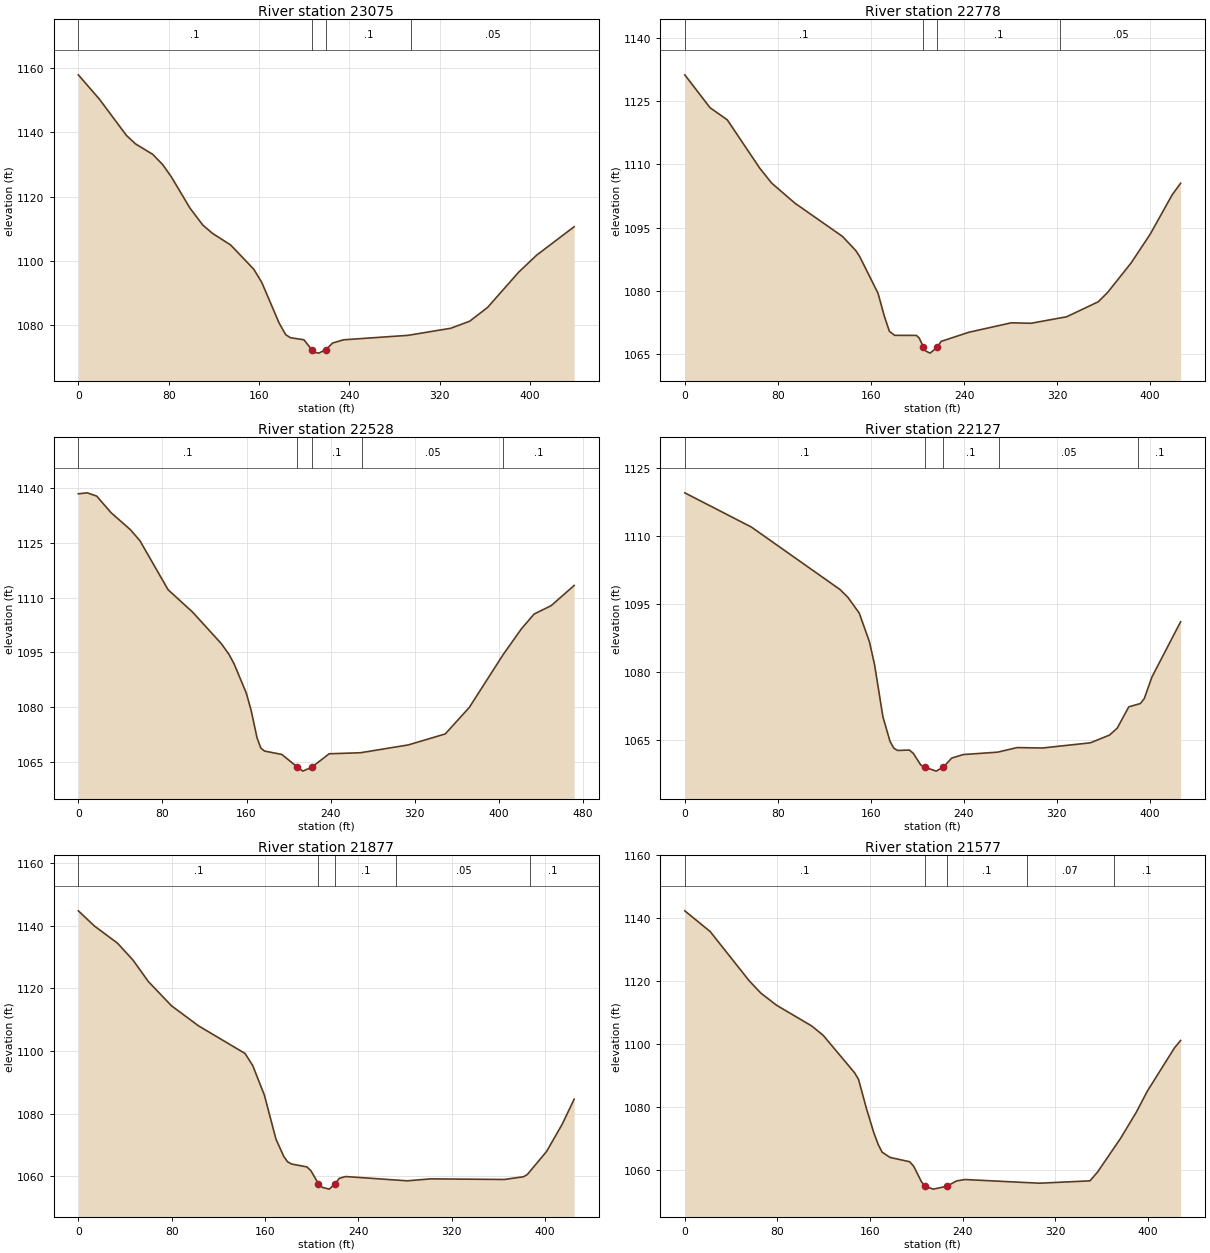
Type RM Length L Ch R = 1 ,23075   ,294.9,296.5,295.8
XS GIS Cut Line= 6
1667933.24995933473620.6504974221667882.89376085473692.208097085
 1667839.7311175 473753.543276251667776.99469443473834.511618257
1667726.45280075473897.6804551781667674.44535884473975.149460346
#Sta/Elev= 30
       0 1157.89    18.8 1150.25    42.6 1139.03    50.6  1136.4    65.9 1133.13
    74.7 1129.94    82.4 1126.11    98.9 1116.38   110.3 1111.09   118.8 1108.53
   134.9 1104.91   155.4 1097.36   162.5 1093.22   177.8 1080.62   183.7 1076.96
   187.9 1076.03   199.8  1075.4  206.751072.282   208.6 1071.55   212.8 1071.24
   219.11072.279   225.2 1074.38   234.9 1075.39     292 1076.78   329.8 1078.98
   346.6 1081.18   362.4 1085.46     390 1096.46   405.8 1101.72   439.1  1110.6
#Mann= 4 ,-1,0
       0      .1       0  206.75    .045       0   219.1      .1       0
  294.93     .05       0
Bank Sta=206.75,219.1
XS Rating Curve= 0 ,0
Exp/Cntr(USF)=0,0
Exp/Cntr=0.3,0.1

Type RM Length L Ch R = 1 ,22778   ,249.6,250.2,250.1
XS GIS Cut Line= 6
1667681.34527943473523.986648753 1667625.2472945473591.290976092
1667573.54136117473645.6186233461667506.30724367473719.680483088
1667460.19545926473779.3325947521667408.03316201473850.431533918
#Sta/Elev= 30
       0 1131.23    21.7 1123.43    36.5 1120.56    64.4  1109.1    74.7 1105.54
    94.7 1100.78   135.5 1092.91     147 1089.54   150.4 1088.09   166.1 1079.42
   171.5 1074.01   175.9 1070.38   180.4 1069.44   199.1 1069.42   201.5  1068.8
  205.161066.638     207 1065.74   210.8 1065.22  217.17 1066.64   220.3    1068
   244.2 1070.17   280.6 1072.41   297.6  1072.3   328.2 1073.84   355.4  1077.4
   363.5 1079.63   383.6 1086.59   400.1 1093.45   418.8 1102.71   426.2 1105.52
#Mann= 4 ,-1,0
       0      .1       0  205.16    .045       0  217.17      .1       0
  322.65     .05       0
Bank Sta=205.16,217.17
XS Rating Curve= 0 ,0
Exp/Cntr(USF)=0,0
Exp/Cntr=0.3,0.1

Type RM Length L Ch R = 1 ,22528   ,403,401.2,392.8
XS GIS Cut Line= 3
1667498.93291458473370.5781629231667267.07455234473610.853003508
1667168.33661144473706.786269398
#Sta/Elev= 30
       0 1138.45     8.4 1138.72    17.5 1137.82    31.2 1133.25    49.5 1128.62
    58.6 1125.58    85.4 1112.14   108.7    1106   136.1 1097.32   143.4 1094.37
   148.1 1091.84   159.7 1083.85   164.3 1079.14     170 1071.51   173.6 1068.71
   177.1  1067.9   193.6 1066.96   208.4 1063.48   213.6 1062.39  222.131063.486
   238.6 1067.15   268.3 1067.43   313.9 1069.58     349 1072.59   371.9 1079.87
   403.9 1094.28   421.5 1101.45   433.5 1105.47   449.8 1107.79   471.6 1113.31
#Mann= 5 ,-1,0
       0      .1       0   208.4    .045       0  222.13      .1       0
     270     .05       0   403.9      .1       0
Bank Sta=208.4,222.13
XS Rating Curve= 0 ,0
Exp/Cntr(USF)=0,0
Exp/Cntr=0.3,0.1

Type RM Length L Ch R = 1 ,22127   ,249.5,249.8,249.8
XS GIS Cut Line= 2
 1667053.7341031473168.9972728081666995.48166242473591.382183254
#Sta/Elev= 30
       0 1119.44    57.3 1111.91   133.4  1098.2   140.1 1096.52     150 1093.02
   158.8 1086.69   163.2 1081.66   170.4 1070.18   176.5  1064.8   179.8 1063.29
   183.1  1062.8     193  1062.9   196.4 1062.21     203 1059.59   206.3 1059.14
   216.2 1058.26  222.451059.161   229.5 1061.12   239.4  1061.9     269 1062.43
   285.8 1063.44   307.4 1063.34   348.7 1064.48   365.3 1066.19   371.9 1067.71
   381.8 1072.39   391.8 1073.12   395.1 1074.19   401.7 1078.94   426.4  1091.1
#Mann= 5 ,-1,0
       0      .1       0   206.3    .045       0  222.45      .1       0
     270     .05       0     390      .1       0
Bank Sta=206.3,222.45
XS Rating Curve= 0 ,0
Exp/Cntr(USF)=0,0
Exp/Cntr=0.3,0.1

Type RM Length L Ch R = 1 ,21877   ,298.5,300,301.1
XS GIS Cut Line= 6
1666813.42247459 473110.48550725 1666801.0481555473197.106068924
1666790.44154942473271.3523115071666776.29886118473370.347192258
1666765.69258317 473444.593434841666753.31760792  473531.2139965
#Sta/Elev= 30
       0  1144.8    13.7 1139.98    33.6 1134.47    46.8  1129.1    60.1 1122.19
    79.9 1114.47   103.1 1108.06   142.9 1099.26   149.5 1095.39   159.5 1085.92
   169.4  1071.9   176.1 1066.38   179.4 1064.66   182.7 1063.96   195.9 1063.04
   199.3 1061.85  205.861057.654   209.2  1056.5     215 1055.94  220.161057.656
   223.7 1059.39   229.1 1059.96   282.1 1058.59     302 1059.22     365 1059.02
   381.5 1059.88   384.8 1060.58   401.4 1067.98   414.7 1076.63     425 1084.66
#Mann= 5 ,-1,0
       0      .1       0  205.86    .045       0  220.16      .1       0
   272.5     .05       0   387.5      .1       0
Bank Sta=205.86,220.16
XS Rating Curve= 0 ,0
Exp/Cntr(USF)=0,0
Exp/Cntr=0.3,0.1

Type RM Length L Ch R = 1 ,21577   ,216.9,217.3,213.9
XS GIS Cut Line= 6
1666541.87708592473079.7142433381666521.99818867473166.037233427
1666504.14061284473240.2303265041666476.50123243473336.624490678
1666460.05146217473409.8392392551666446.86710534473496.685194179
#Sta/Elev= 30
       0 1142.38    21.9 1135.81    55.6 1120.17    65.7 1116.25    79.1 1112.43
   109.5 1105.84   119.6 1102.81   146.6 1090.95     150 1088.87   156.7 1079.78
   163.1 1072.03   166.9 1068.26   170.3 1065.78   177.1 1064.09   194.2  1062.7
   197.6 1061.29   204.4 1056.32  207.46 1054.91   214.6 1054.01  226.091054.908
   234.7 1056.62   241.9 1057.06   306.2 1055.89   349.8 1056.64   356.4 1059.44
   376.3 1070.16   389.8 1078.42   399.5 1085.21   422.8 1098.87   428.1 1101.21
#Mann= 5 ,-1,0
       0      .1       0  207.46    .045       0  226.09      .1       0
  295.17     .07       0  370.21      .1       0
Bank Sta=207.46,226.09
XS Rating Curve= 0 ,0
Exp/Cntr(USF)=0,0
Exp/Cntr=0.3,0.1

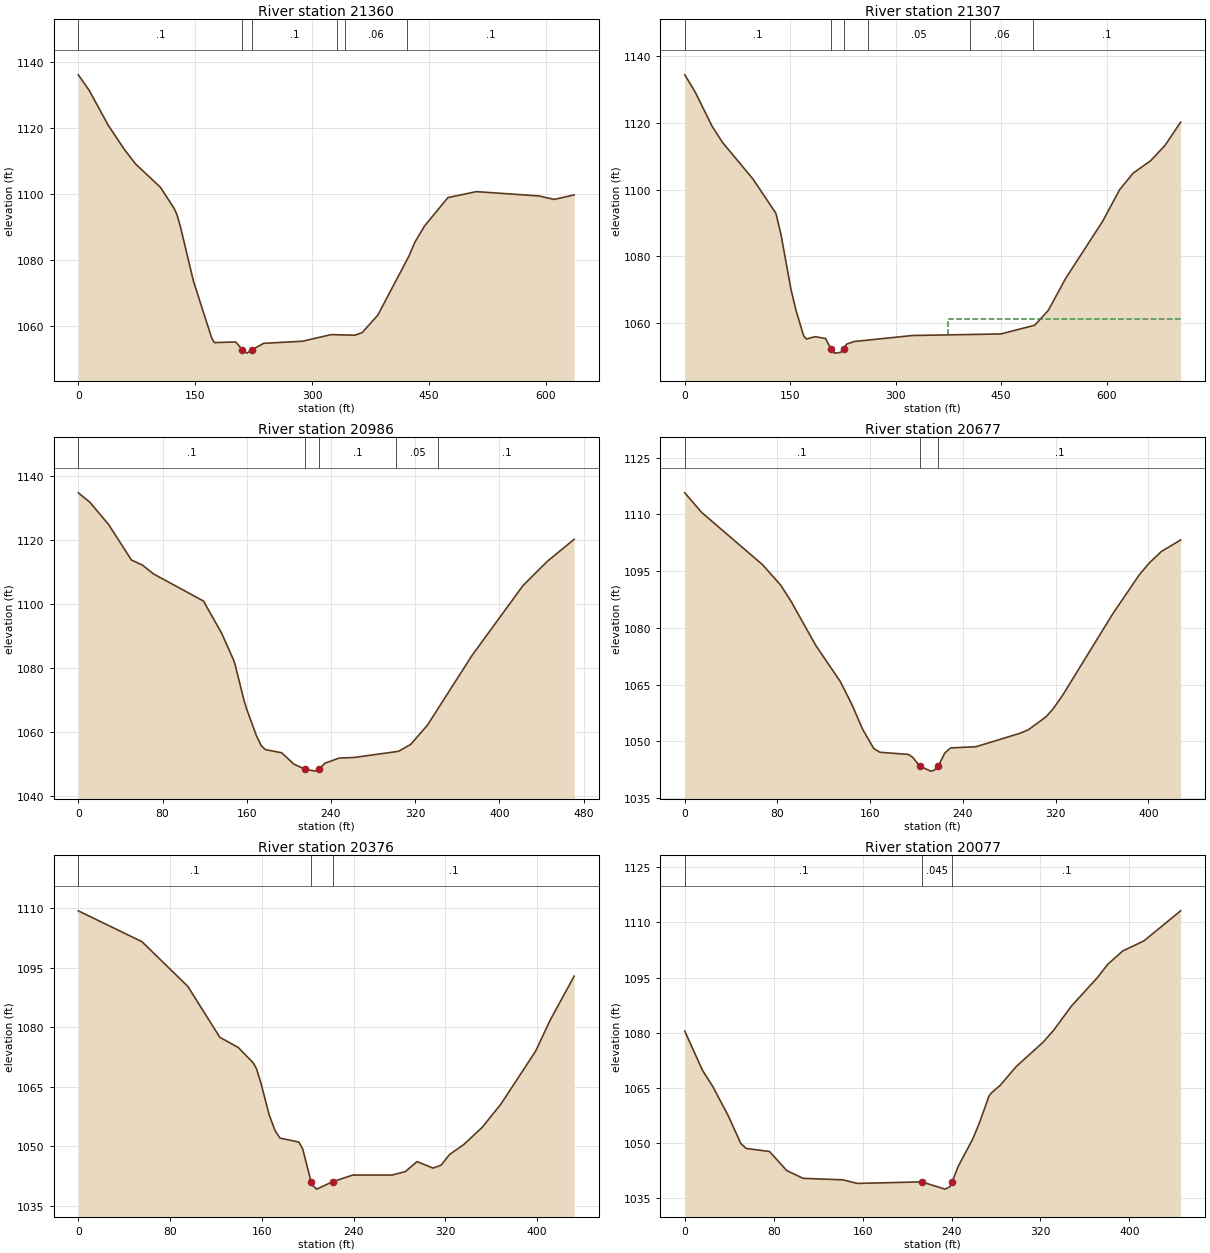
Type RM Length L Ch R = 1 ,21360   ,49.5,52.5,54.2
XS GIS Cut Line= 3
1666350.08613417473055.407515673 1666294.6823619473197.020284401
1666210.97205231473674.033732651
#Sta/Elev= 30
       0 1136.03    13.8  1131.4    38.4 1120.78    59.6  1113.3    73.7 1109.03
   105.4 1102.03     123 1095.65   126.5 1093.83   130.9 1090.26   147.7  1073.7
   171.2 1056.45   174.5 1055.09   202.1 1055.27   210.6  1052.9   216.3  1051.9
  222.941052.895   237.8 1054.86   287.8  1055.5   324.4 1057.49   355.1 1057.32
   364.4 1058.12   384.4 1063.39   424.4 1081.26   431.6 1085.27   444.3 1090.31
   474.3 1098.91   510.9 1100.72   590.9 1099.42   610.9 1098.37   636.4 1099.73
#Mann= 6 ,-1,0
       0      .1       0   210.6    .045       0  222.94      .1       0
  332.06     .05       0  342.06     .06       0  422.06      .1       0
Bank Sta=210.6,222.94
XS Rating Curve= 0 ,0
Exp/Cntr(USF)=0,0
Exp/Cntr=0.3,0.1

Type RM Length L Ch R = 1 ,21307   ,318.7,321.6,324.9
XS GIS Cut Line= 3
1666323.51531792473048.5994761741666181.77330987  473363.7476766
1665937.38319255 473627.74541672
#Sta/Elev= 30
       0 1134.42    14.3 1129.45    38.9    1119    53.8 1114.11    97.1 1103.17
   129.5 1092.98   136.7 1086.72     151 1070.17   158.2 1063.86     169 1056.26
   172.9 1055.26   185.3 1055.96   200.2 1055.41   207.7 1052.41   212.6 1051.03
   221.6 1051.24  225.881052.414   230.2 1053.72     241 1054.51   323.7 1056.31
   449.4 1056.77   497.7 1059.38     517 1063.82   541.9 1073.47   594.3  1090.5
   618.4 1099.96   637.7 1104.95   662.7 1108.69   683.2 1113.31   705.3 1120.24
#Mann= 6 ,-1,0
       0      .1       0   207.7    .045       0  225.88      .1       0
     260     .05       0  405.56     .06       0  495.56      .1       0
#XS Ineff= 2 , 0
                          373.72         1061.23
Permanent Ineff=
       F       F
Bank Sta=207.7,225.88
XS Rating Curve= 0 ,0
Exp/Cntr(USF)=0,0
Exp/Cntr=0.3,0.1

Type RM Length L Ch R = 1 ,20986   ,310.4,308.7,304.7
XS GIS Cut Line= 3
1666156.12306173472910.8454811891665932.98365194473099.352561719
1665806.37757267473225.694235291
#Sta/Elev= 30
       0 1134.77    10.8 1131.89    28.7 1124.88    50.4 1113.76    60.9 1112.14
    71.6 1109.35   118.9 1100.89   136.1 1090.84   147.3 1082.58   148.9 1081.01
   157.5 1069.66   159.8  1067.2   169.1  1058.8   173.8 1055.59   177.8 1054.37
   193.1 1053.41   204.8 1049.83  215.021048.292     225 1047.65228.58941048.297
   234.3 1050.14   247.7 1051.73   262.3 1051.93   304.1 1053.85   315.7 1056.01
   331.7 1062.07     374 1083.87   422.4 1105.74   445.6 1113.35     471 1120.22
#Mann= 5 ,-1,0
       0      .1       0  215.02    .045       0228.5894      .1       0
  302.11     .05       0  342.11      .1       0
Bank Sta=215.02,228.5894
XS Rating Curve= 0 ,0
Exp/Cntr(USF)=0,0
Exp/Cntr=0.3,0.1

Type RM Length L Ch R = 1 ,20677   ,296.8,300.7,299.2
XS GIS Cut Line= 6
1665861.71276385472699.7268143451665805.54489717472768.375955254
1665765.50068593472832.0080458371665722.01783326472922.132537499
1665683.55071859472987.3666590011665637.66924867473062.773660421
#Sta/Elev= 30
       0 1115.72    14.6 1110.52    67.1 1096.72    82.6 1091.37    91.6 1087.08
     113  1075.4   134.4 1065.72   144.5 1059.55   153.5 1053.19     163 1048.13
   168.5 1047.11     193 1046.55   196.7 1045.79  202.64 1043.49   212.1 1042.13
   214.9 1042.31  218.781043.492   224.4 1046.92   229.3 1048.26   251.3 1048.59
   288.8 1052.09   296.5 1053.06   311.7 1056.48     318 1058.66     326 1062.15
   369.2 1083.66   392.1 1093.99   400.5 1097.06   411.3 1100.21   427.9 1103.25
#Mann= 3 ,-1,0
       0      .1       0  202.64    .045       0  218.78      .1       0
Bank Sta=202.64,218.78
XS Rating Curve= 0 ,0
Exp/Cntr(USF)=0,0
Exp/Cntr=0.3,0.1

Type RM Length L Ch R = 1 ,20376   ,292.4,298.9,297.5
XS GIS Cut Line= 6
1665680.54580334 472478.051404671665630.61250426472549.904935509
1665587.81272109472611.4937230941665529.56775884472692.793101177
1665476.17219634472750.2067002511665411.70021242472814.984129757
#Sta/Elev= 30
       0 1109.28    55.5 1101.51    95.5 1090.26   123.4 1077.45   139.4  1074.9
   152.3  1071.1   155.4 1069.53   159.4 1065.75   166.4 1057.95   171.5 1054.01
   175.8  1052.1   192.3 1051.11   195.7  1049.3  202.941041.118   203.7 1040.35
   207.8 1039.26  221.641041.115   239.3  1042.8   273.4 1042.79   285.2 1043.68
   295.3 1046.18   309.3 1044.56   316.2 1045.27   323.7 1047.98   336.2 1050.51
   352.2 1054.84   368.4 1060.64   398.7 1073.97   411.4 1081.79   432.3 1092.84
#Mann= 3 ,-1,0
       0      .1       0  202.94    .045       0  221.64      .1       0
Bank Sta=202.94,221.64
XS Rating Curve= 0 ,0
Exp/Cntr(USF)=0,0
Exp/Cntr=0.3,0.1

Type RM Length L Ch R = 1 ,20077   ,299.7,308.5,301
XS GIS Cut Line= 6
1665459.16402826472354.3183844241665386.36364892472423.702432007
1665331.22497967472485.799748749 1665264.8999811 472560.69756484
  1665214.017865472615.798832595 1665154.6656215472680.069701418
#Sta/Elev= 30
       0 1080.43    15.9 1069.83    25.2  1065.4    39.1 1057.46    50.4 1049.93
    55.3 1048.59    76.2 1047.76    91.7 1042.59   106.4 1040.47   142.1 1040.07
   155.2 1039.09   213.3 1039.51   234.1 1037.54   238.5 1038.18  240.591039.511
   245.8 1043.61   259.1 1051.16   264.8 1055.32   273.7 1062.82   276.1 1063.75
   283.7 1065.72   298.3 1070.87   322.5 1077.47   332.2 1080.82     348 1087.31
   370.9 1094.87   380.5 1098.59     394 1102.22   413.1 1104.96   446.1 1113.12
#Mann= 3 ,-1,0
       0      .1       0   213.3    .045       0  240.59      .1       0
Bank Sta=213.3,240.59
XS Rating Curve= 0 ,0
Exp/Cntr(USF)=0,0
Exp/Cntr=0.3,0.1

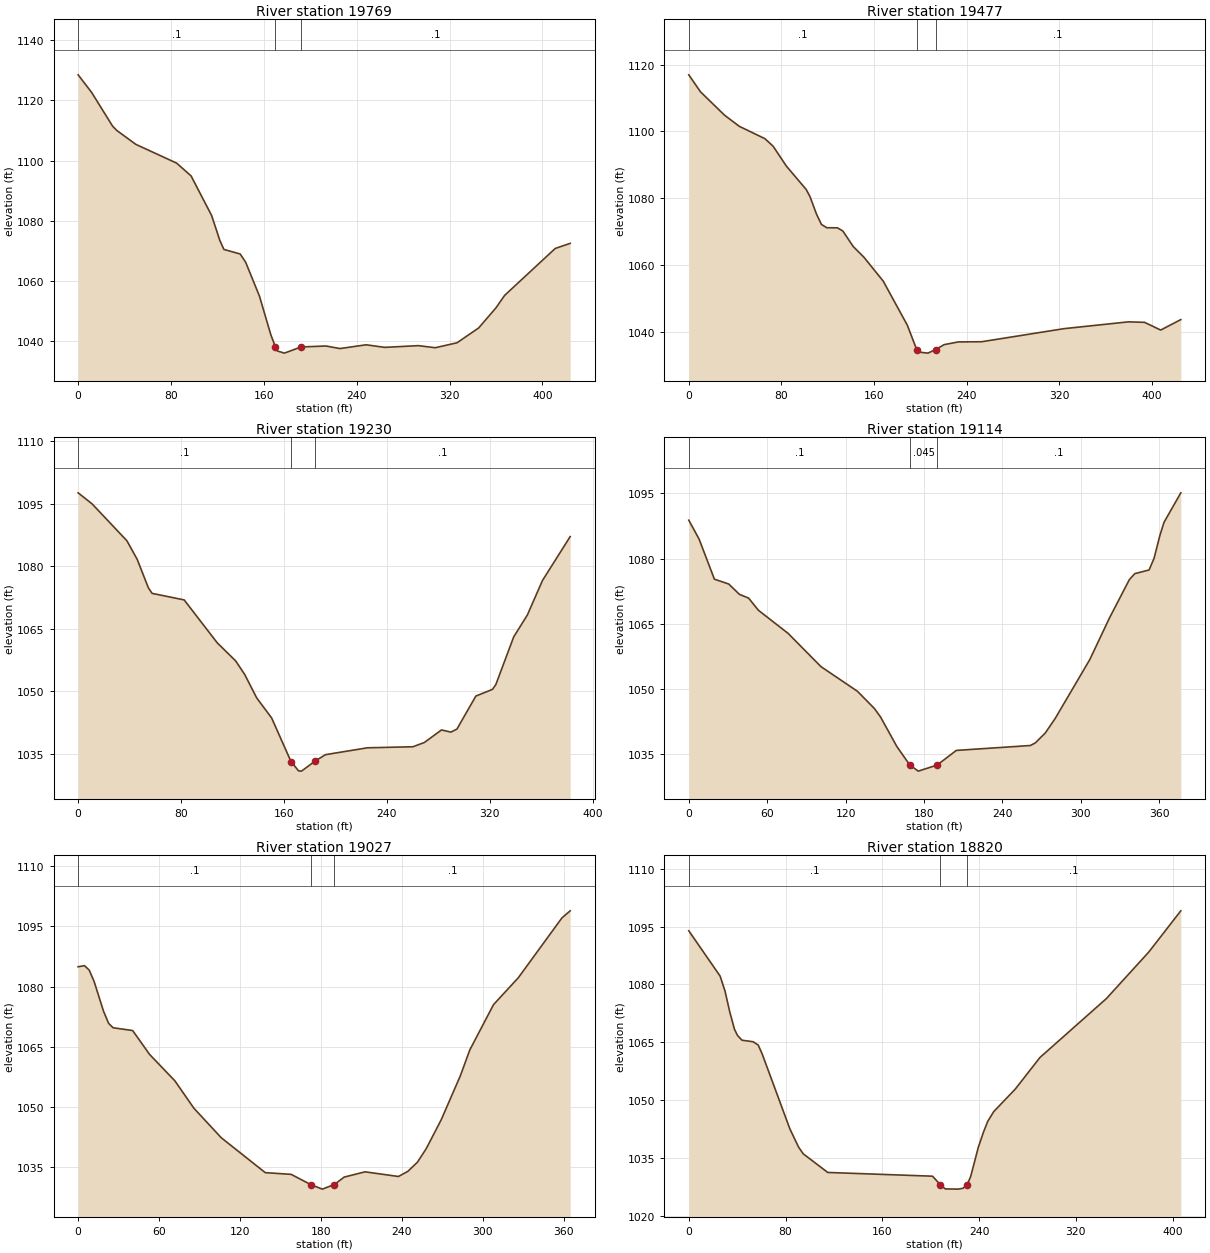
Type RM Length L Ch R = 1 ,19769   ,287.3,291.8,290.7
XS GIS Cut Line= 5
1665257.54630404472125.8946400391665235.66972458472175.024123594
1665207.11367933 472244.375034751665153.98911367472330.437854752
1665061.84633942472501.097623956
#Sta/Elev= 30
       0 1128.52    11.6 1122.68    29.6 1111.49    33.2 1110.03    49.7 1105.38
    84.9 1099.12    97.3 1094.87     115 1081.71   122.1 1073.37   125.6  1070.4
   139.6 1068.89   144.4 1066.08   156.2 1054.87     166 1042.02  169.961037.973
   171.6 1036.61   177.7 1035.89     192 1037.94   213.5 1038.26   225.6 1037.41
   248.1 1038.66   264.1 1037.81   293.1 1038.38   307.7 1037.69   326.4 1039.33
   345.1 1044.28     360 1050.98   367.4 1055.09     411 1070.72   423.9 1072.43
#Mann= 3 ,-1,0
       0      .1       0  169.96    .045       0     192      .1       0
Bank Sta=169.96,192
XS Rating Curve= 0 ,0
Exp/Cntr(USF)=0,0
Exp/Cntr=0.3,0.1

Type RM Length L Ch R = 1 ,19477   ,247.2,247.4,246.9
XS GIS Cut Line= 6
1665066.11822642472005.5976251661665007.54485276472070.767770424
  1664955.805783472125.0944334271664885.09496643472195.805578083
1664832.06226408472248.8389365821664770.18968442472310.709875837
#Sta/Elev= 30
       0 1116.95    10.1 1111.87      31 1104.83    43.7 1101.52    65.8 1097.82
    72.8  1095.6    84.4 1089.58   101.4 1082.63   104.7  1080.5   110.4 1075.19
   114.6 1072.15   119.2 1071.16   128.5 1071.12   133.1 1070.18   142.1 1065.52
   151.2 1062.37     168 1055.16   188.8 1041.98  196.941034.642   198.9 1033.91
   206.6  1033.6  213.181034.641   220.5 1036.13   232.9 1036.96     253 1037.01
   324.2 1040.93   379.9 1042.97   393.8 1042.82   407.7 1040.51   425.1 1043.64
#Mann= 3 ,-1,0
       0      .1       0  196.94    .045       0  213.18      .1       0
Bank Sta=196.94,213.18
XS Rating Curve= 0 ,0
Exp/Cntr(USF)=0,0
Exp/Cntr=0.3,0.1

Type RM Length L Ch R = 1 ,19230   ,111.9,115.8,118.6
XS GIS Cut Line= 2
  1664862.026299471862.4513791651664603.97695898472144.653120469
#Sta/Elev= 30
       0 1097.66    10.9 1094.99    37.9 1086.15    45.9 1081.69    54.6 1074.84
    57.5 1073.52    82.4 1071.95   108.1 1061.65   122.5 1057.28   129.5 1054.02
   138.8 1048.41   150.4  1043.6  165.421033.151   171.3 1030.91   173.6 1030.84
  183.711033.154   192.2 1034.79   224.8 1036.44   260.2 1036.69   269.1 1037.72
   282.4 1040.73   289.7 1040.21   294.4 1040.94   309.1 1048.86     322 1050.47
   324.6  1051.6   338.5 1063.06   349.1 1068.31   360.9 1076.62   382.4 1087.15
#Mann= 3 ,-1,0
       0      .1       0  165.42    .045       0  183.71      .1       0
Bank Sta=165.42,183.71
XS Rating Curve= 0 ,0
Exp/Cntr(USF)=0,0
Exp/Cntr=0.3,0.1

Type RM Length L Ch R = 1 ,19114   ,84.6,87.1,86.1
XS GIS Cut Line= 2
1664809.06968351471831.2299383821664482.63258042 472019.12606702
#Sta/Elev= 30
       0 1088.83     7.9 1084.47    19.6 1075.24    30.6 1074.12    38.8 1071.74
    45.8 1070.88    53.3 1068.08    76.1 1062.74   101.2 1055.09   129.1 1049.42
   142.1 1045.45   146.9 1043.45   159.3 1036.69  169.251032.423   175.7 1031.02
  190.181032.423   204.8 1035.79   261.5 1036.92   265.3 1037.52   272.9 1039.79
   280.5 1043.14     307 1056.71   322.1 1066.31   337.3 1075.13   341.5 1076.52
   352.4 1077.36   356.2 1080.03   360.7 1085.32   363.8 1088.31   376.7 1095.13
#Mann= 3 ,-1,0
       0      .1       0  169.25    .045       0  190.18      .1       0
Bank Sta=169.25,190.18
XS Rating Curve= 0 ,0
Exp/Cntr(USF)=0,0
Exp/Cntr=0.3,0.1

Type RM Length L Ch R = 1 ,19027   ,206.8,207,209.1
XS GIS Cut Line= 2
1664770.50140993471789.9941753171664431.09661295 471923.46797188
#Sta/Elev= 30
       0 1084.95     4.7 1085.23     8.2 1084.12    11.8 1081.33    18.8 1073.89
    22.6 1070.85    25.9 1069.75    40.4 1069.06      53 1063.09    71.7 1056.53
    85.8  1049.7   106.1 1042.34   138.7 1033.65   157.9 1033.22  172.331030.684
     181 1029.54  189.931030.685   197.2 1032.54   212.7 1033.85   237.4 1032.69
   244.4 1033.97   251.5 1036.25     258 1039.62   269.1 1046.81   283.3 1057.78
   290.3 1064.22   307.9 1075.52   326.3 1082.23   358.6 1097.13   364.7 1098.89
#Mann= 3 ,-1,0
       0      .1       0  172.33    .045       0  189.93      .1       0
Bank Sta=172.33,189.93
XS Rating Curve= 0 ,0
Exp/Cntr(USF)=0,0
Exp/Cntr=0.3,0.1

Type RM Length L Ch R = 1 ,18820   ,241.9,242.7,244.3
XS GIS Cut Line= 4
 1664675.8898662471599.8147191211664640.67714232471624.069517153
1664574.33639574471661.5195734971664304.99122032471763.136714862
#Sta/Elev= 30
       0 1093.89    25.9 1082.16    29.9 1078.35    33.9 1072.86    37.8 1068.36
    40.3 1066.78      44 1065.55    53.2 1065.15    57.4  1064.3    60.7 1061.98
    83.6 1042.57    90.8 1037.85    94.6 1036.13   114.9  1031.3   201.5 1030.33
  207.851028.169     212 1027.04   222.5 1026.98   226.7 1027.19  230.171028.173
   233.1 1030.28   239.4 1037.84   243.6  1041.7   247.1 1044.49   252.1 1047.05
     270 1052.91   290.3 1061.06   345.3 1076.34   380.3 1088.38   406.8 1099.06
#Mann= 3 ,-1,0
       0      .1       0  207.85    .045       0  230.17      .1       0
Bank Sta=207.85,230.17
XS Rating Curve= 0 ,0
Exp/Cntr(USF)=0,0
Exp/Cntr=0.3,0.1