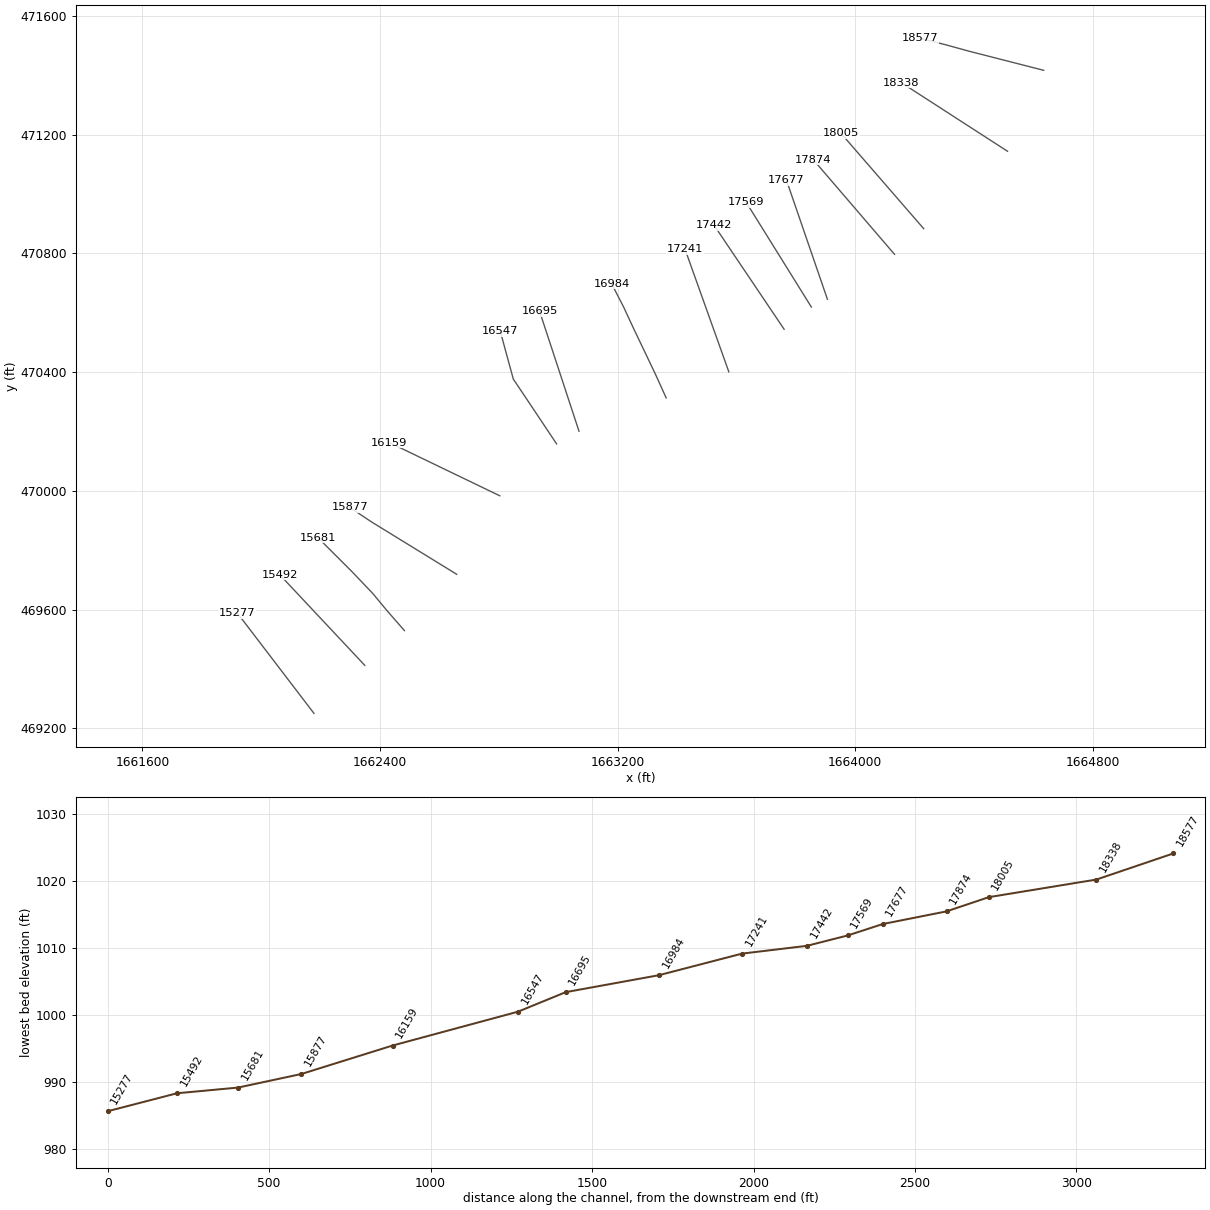
HEC-RAS study BigRnI.prj: BigRnI

--- BigRnI.g01 (geometry) --- (continued)

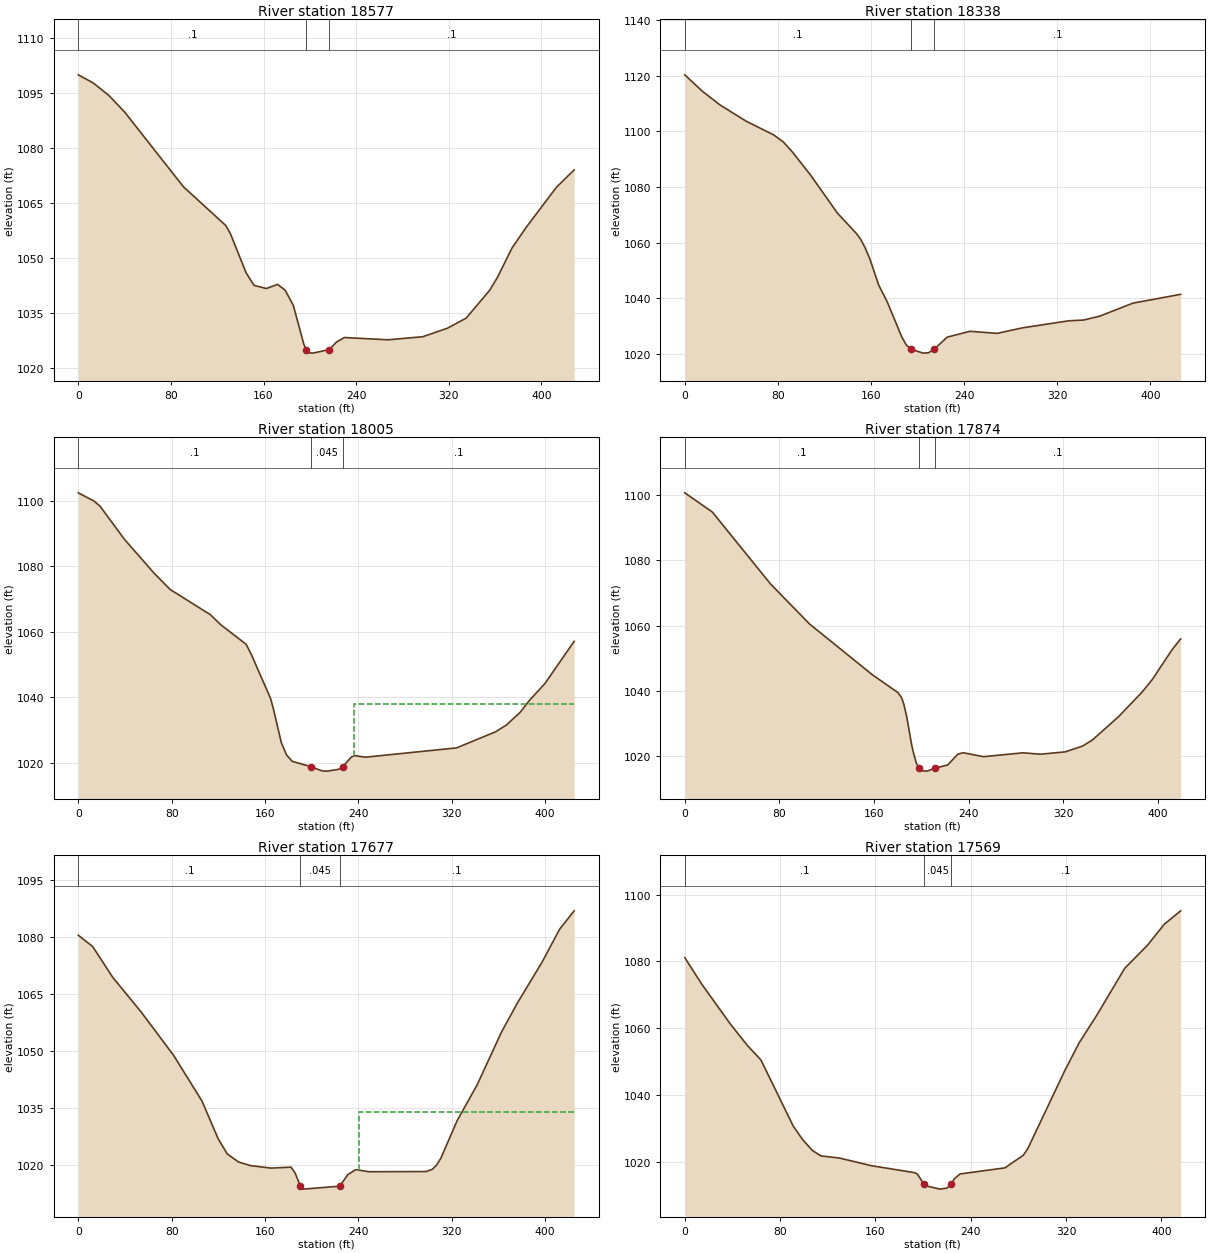
Type RM Length L Ch R = 1 ,18577   ,240.6,238.5,234.5
XS GIS Cut Line= 6
1664634.27919509471416.5397481771664549.52083443471438.271332011
1664476.87071726 471456.898591341664380.00411309471481.735155836
1664307.27459976471501.8355093451664219.76854117471524.306593001
#Sta/Elev= 30
       0 1099.85    12.9 1097.63    26.5  1094.2      40 1089.71    90.8 1069.36
   127.4  1058.8   131.5 1056.49     145 1045.89   151.8 1042.51   162.4 1041.65
   172.1 1042.78   178.6 1041.22   185.7 1037.08   194.8 1026.46  196.85 1025.04
   199.2 1024.17   202.6 1024.06  216.951025.039   222.9 1027.06   229.8 1028.31
   267.5 1027.69   297.6 1028.53   318.8 1030.84     335 1033.59   355.4  1041.2
   362.2 1044.79   374.6 1052.68   386.7 1058.25     413 1069.23   428.3 1073.97
#Mann= 3 ,-1,0
       0      .1       0  196.85    .045       0  216.95      .1       0
Bank Sta=196.85,216.95
XS Rating Curve= 0 ,0
Exp/Cntr(USF)=0,0
Exp/Cntr=0.3,0.1

Type RM Length L Ch R = 1 ,18338   ,334.8,333.4,329.7
XS GIS Cut Line= 2
1664512.44722188471143.8940079681664154.77404135471375.094304379
#Sta/Elev= 30
       0  1120.4    14.8 1114.59      30 1109.63    52.7  1103.7    76.5 1098.73
    84.7  1096.2    92.5 1092.58   108.1 1084.26     131 1070.64   147.7 1063.12
   151.1 1061.12   154.8  1058.2   158.9 1054.16   166.6 1044.64   173.8  1038.7
   186.3 1026.07   190.2 1023.14  194.431021.591   204.6 1020.16   209.3 1020.28
  214.341021.593   225.3 1025.91   244.9 1028.02   268.3 1027.28     290 1029.26
   329.7  1031.8   342.5 1032.07   356.5 1033.49   384.9 1038.16   425.9 1041.34
#Mann= 3 ,-1,0
       0      .1       0  194.43    .045       0  214.34      .1       0
Bank Sta=194.43,214.34
XS Rating Curve= 0 ,0
Exp/Cntr(USF)=0,0
Exp/Cntr=0.3,0.1

Type RM Length L Ch R = 1 ,18005   ,130.2,130.8,131.2
XS GIS Cut Line= 6
1664230.42275377470882.8981966991664173.11578178470949.020439776
1664123.99580128 471005.696835611664058.50249394471081.265582117
1664009.38251344 471137.941977951663952.07586952471204.064549121
#Sta/Elev= 30
       0 1102.45    13.5 1099.91    18.6 1098.38    39.5 1088.27    64.7 1078.03
    78.6 1072.99   113.3 1065.23     122 1062.22   143.8 1056.24     148 1053.35
   164.7 1039.77     167 1036.82     174 1026.22   178.4 1022.51   183.3 1020.52
  199.341018.901   208.9  1017.6   213.2 1017.53   222.9 1018.06  226.72  1018.9
     234 1021.82   236.8 1022.26   246.1 1021.78   324.2 1024.62   357.8 1029.55
   367.1 1031.65   378.7 1035.47   386.8 1039.17   399.9 1044.23     425 1057.14
#Mann= 3 ,-1,0
       0      .1       0  199.34    .045       0  226.72      .1       0
#XS Ineff= 1 ,-1
  236.29   424.9 1037.92
Permanent Ineff=
       F
Bank Sta=199.34,226.72
XS Rating Curve= 0 ,0
Exp/Cntr(USF)=0,0
Exp/Cntr=0.3,0.1

Type RM Length L Ch R = 1 ,17874   ,204.1,197.4,193.7
XS GIS Cut Line= 2
1664132.05030628470796.6596823631663859.28632859471114.712773337
#Sta/Elev= 30
       0 1100.68    23.3 1094.79    72.4 1072.78   105.4  1060.5   158.5 1044.94
   180.1 1039.48   183.2 1037.91   185.1  1035.9   187.5 1032.13   191.8  1023.3
   193.4 1020.81   195.7 1017.83   198.11016.312   200.2 1015.52   204.8 1015.41
  211.441016.318   222.1 1017.28   230.6 1020.56   235.1 1021.06   252.3 1019.84
   285.9 1021.02   300.4 1020.59   321.4  1021.3   336.3 1023.11   344.6    1025
   366.6 1032.12   386.5 1039.66     395 1043.45   411.9 1052.68     419 1055.93
#Mann= 3 ,-1,0
       0      .1       0   198.1    .045       0  211.44      .1       0
Bank Sta=198.1,211.44
XS Rating Curve= 0 ,0
Exp/Cntr(USF)=0,0
Exp/Cntr=0.3,0.1

Type RM Length L Ch R = 1 ,17677   ,104.4,108.4,110.5
XS GIS Cut Line= 6
 1663906.1763206470645.1964745821663877.73116751470727.943684429
1663853.34965459470798.8700517571663820.84118943470893.438432172
1663796.46033268470964.3651275931663768.01517959471047.112337425
#Sta/Elev= 30
       0 1080.51    12.3 1077.53    29.5 1069.41      54  1060.2    81.7 1048.81
     106 1036.76   119.9 1026.78   127.6 1022.83   137.2  1020.7   147.6 1019.72
     165 1019.07   182.3 1019.32   185.8 1017.78  190.391014.292   192.7 1013.52
   224.11014.295   230.9 1017.31   237.8 1018.67     249 1018.11     298 1018.16
   303.2 1018.71   307.2 1019.89   310.7 1021.66   324.6 1031.52   341.9 1041.07
   362.7 1054.96   376.6 1062.76   397.4 1073.37   412.6 1082.13     425 1086.96
#Mann= 3 ,-1,0
       0      .1       0  190.39    .045       0   224.1      .1       0
#XS Ineff= 2 , 0
                          240.25         1033.96
Permanent Ineff=
       F       F
Bank Sta=190.39,224.1
XS Rating Curve= 0 ,0
Exp/Cntr(USF)=0,0
Exp/Cntr=0.3,0.1

Type RM Length L Ch R = 1 ,17569   ,125.6,126.4,126.6
XS GIS Cut Line= 2
 1663852.1212457 470618.983131691663632.46021775470972.334618433
#Sta/Elev= 30
       0 1081.13    14.2 1073.21      38 1061.37    52.3 1054.93    63.9 1050.49
    90.9 1030.76    98.7 1026.72   107.1 1023.39   114.2 1021.77   129.6 1021.14
   156.6 1018.84   192.8 1016.75   195.2 1016.32  200.511013.402     203 1012.75
   214.3 1011.82   220.1 1012.13   223.8 1013.42   226.2 1014.91     231 1016.36
   268.6 1018.18   284.1 1021.97     288 1024.05   319.1 1047.46     331 1055.66
   345.9 1063.97   369.1  1077.9   388.2 1084.81   402.5 1091.17   416.1 1095.15
#Mann= 3 ,-1,0
       0      .1       0  200.51    .045       0   223.8      .1       0
Bank Sta=200.51,223.8
XS Rating Curve= 0 ,0
Exp/Cntr(USF)=0,0
Exp/Cntr=0.3,0.1

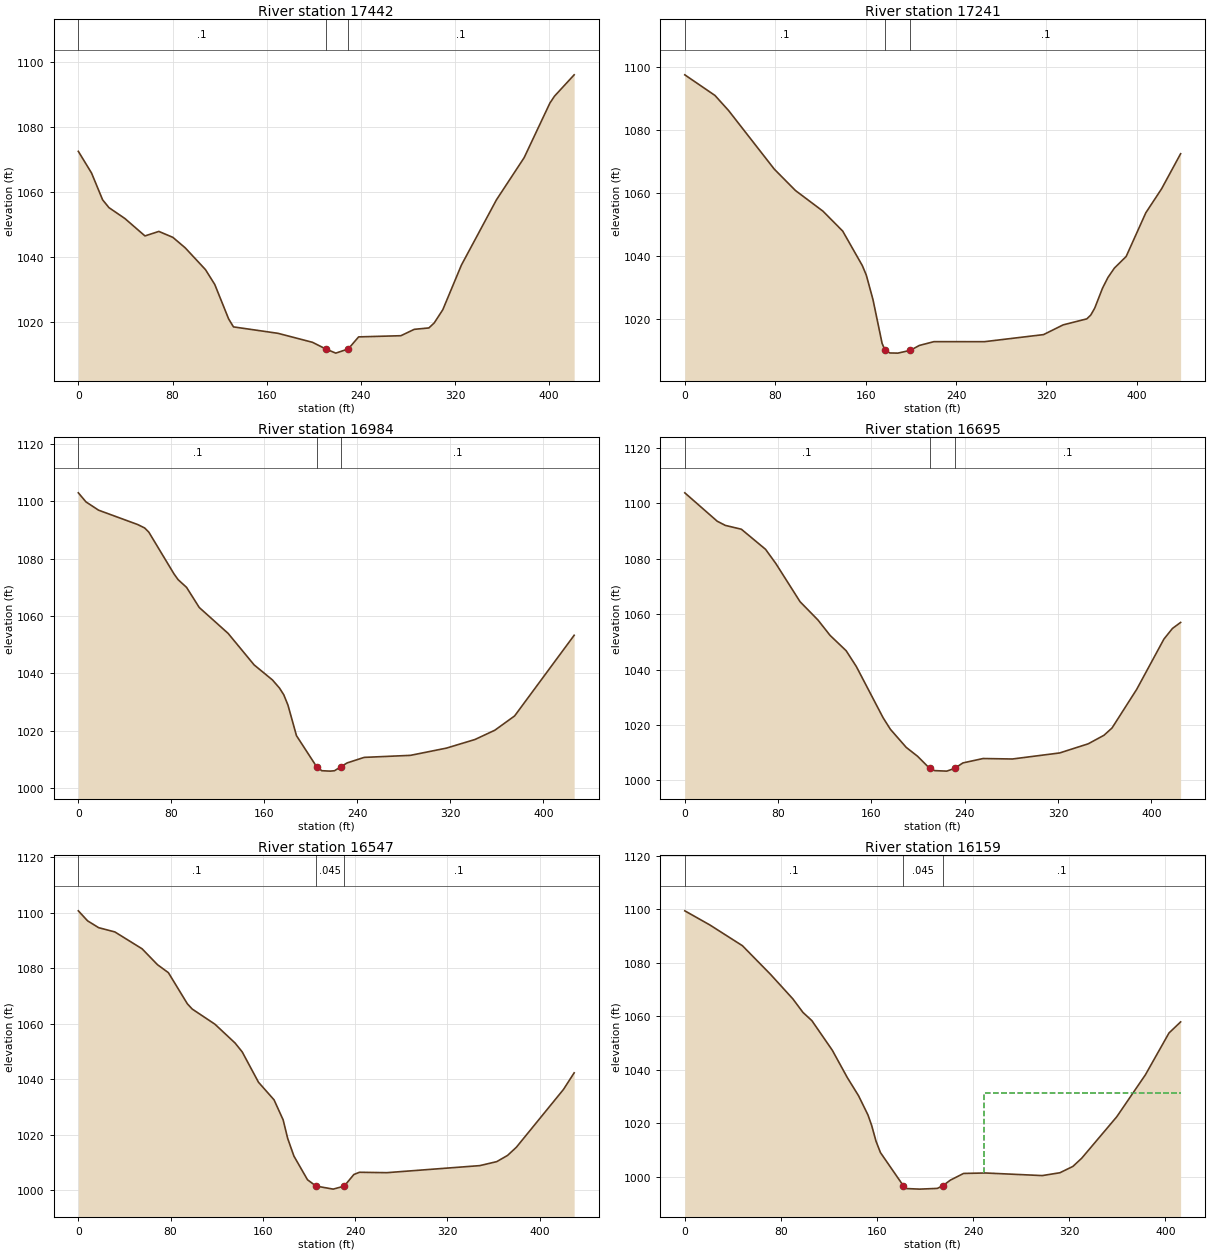
Type RM Length L Ch R = 1 ,17442   ,203.1,200.8,196.6
XS GIS Cut Line= 2
 1663760.3212292470544.3037618861663525.23464232470893.756796436
#Sta/Elev= 30
       0 1072.51    11.2 1065.84    20.6 1057.58      26 1055.15    39.6 1051.78
    56.6 1046.42    68.4 1047.81    80.3 1045.98    90.7 1042.78     108 1036.03
   115.9 1031.45   127.7 1020.81   131.8 1018.36   169.6 1016.38   198.9 1013.61
  210.251011.545   218.7 1010.27  229.311011.563   238.1 1015.28     274 1015.64
   285.4 1017.61   297.8 1018.04   302.3 1019.57   309.6 1023.65   325.4 1037.41
   355.2 1057.56   378.7 1070.55   400.6  1087.4   404.5 1089.53   421.2 1096.11
#Mann= 3 ,-1,0
       0      .1       0  210.25    .045       0  229.31      .1       0
Bank Sta=210.25,229.31
XS Rating Curve= 0 ,0
Exp/Cntr(USF)=0,0
Exp/Cntr=0.3,0.1

Type RM Length L Ch R = 1 ,17241   ,254.9,257.3,257.2
XS GIS Cut Line= 2
1663574.32195692470400.595512052 1663426.8651912470813.728691888
#Sta/Elev= 30
       0 1097.64    26.7 1091.08    38.7  1086.3    79.2 1067.63    97.9 1060.84
   122.3 1054.25   139.7 1047.94   157.1 1036.94   160.6 1033.92   166.5 1026.14
   174.6 1012.17  177.271009.993   181.5 1009.16   188.5 1009.11  199.561009.996
   207.5 1011.55   220.4 1012.76   265.1 1012.75   317.4    1015   334.8  1018.1
   355.7 1020.01   359.2 1021.22   362.7 1023.43   369.6 1029.78   374.4 1033.18
   380.1 1036.16   390.5 1039.85   407.9 1053.75   421.9 1061.41   438.7 1072.54
#Mann= 3 ,-1,0
       0      .1       0  177.27    .045       0  199.56      .1       0
Bank Sta=177.27,199.56
XS Rating Curve= 0 ,0
Exp/Cntr(USF)=0,0
Exp/Cntr=0.3,0.1

Type RM Length L Ch R = 1 ,16984   ,290,288.7,287.2
XS GIS Cut Line= 6
1663363.32447464470312.9248583251663327.20840514470392.642546662
1663294.93615997470460.344182917 1663251.8532409470550.587768831
1663220.18237247470618.8418974061663179.65194172470697.659981244
#Sta/Elev= 30
       0 1102.96     6.6 1099.79    17.4 1096.91    51.1 1091.89      57 1090.71
    60.6 1089.26    82.2 1074.73    85.8 1072.68    93.1 1069.97     104 1062.96
   128.8 1053.94   151.2 1042.93   166.9 1037.71     173 1034.86   176.7  1032.5
   180.3 1028.89   187.6 1018.26  204.881007.458   209.4 1006.03   216.7 1005.89
   220.3 1006.03     2261007.457   231.2 1008.76   245.8 1010.68   285.6 1011.39
   316.5 1013.91   341.1 1016.92   358.2 1020.16   375.2 1025.14   426.4 1053.27
#Mann= 3 ,-1,0
       0      .1       0  204.88    .045       0     226      .1       0
Bank Sta=204.88,226
XS Rating Curve= 0 ,0
Exp/Cntr(USF)=0,0
Exp/Cntr=0.3,0.1

Type RM Length L Ch R = 1 ,16695   ,143.6,148.1,149.8
XS GIS Cut Line= 6
1663069.88384607470200.6877572351663042.57058048470283.815543737
 1663019.1588819470355.0680259131662987.94372123470450.071116741
1662964.53202265470521.3235989021662937.21875706470604.451385404
#Sta/Elev= 30
       0 1103.81    27.8 1093.56    34.7 1092.06    48.5 1090.67    69.2 1083.43
      78 1078.32    98.8 1064.51   114.1 1057.93   124.5 1052.37   138.3 1046.82
     147 1041.14     170 1022.61   176.3 1018.42   189.8 1011.93   199.5 1008.73
  209.831004.374   214.2 1003.54   224.6 1003.36  231.331004.373   238.4 1006.32
   255.7 1007.91   280.8 1007.74   321.3 1009.92   345.8 1013.22   359.3  1016.3
   366.2 1018.93   387.4 1032.91   410.7 1051.03     418 1054.86     425 1057.03
#Mann= 3 ,-1,0
       0      .1       0  209.83    .045       0  231.33      .1       0
Bank Sta=209.83,231.33
XS Rating Curve= 0 ,0
Exp/Cntr(USF)=0,0
Exp/Cntr=0.3,0.1

Type RM Length L Ch R = 1 ,16547   ,374.1,388.3,391.4
XS GIS Cut Line= 5
 1662994.4087927 470158.070796731662945.87181629470230.874784978
1662904.26888112470293.2785315681662848.66925478 470376.41616057
1662804.66842156470537.909408117
#Sta/Elev= 30
       0 1100.72       8 1097.12    17.6 1094.65    31.7 1093.11    55.3 1087.03
    68.6 1081.32    78.1 1078.43    94.5 1067.24    98.7 1065.34   118.4 1059.88
   135.9 1053.09   142.1 1049.88   156.2 1038.96   169.7 1032.61   177.6 1025.37
   181.5 1018.73   186.9 1012.37   198.7 1003.81  206.111001.539     221 1000.44
  230.561001.538   238.9 1005.71   243.7 1006.51   267.5 1006.37   348.1 1008.91
   362.8 1010.35   372.2  1012.6   379.8 1015.53   420.6 1036.34   429.9 1042.34
#Mann= 3 ,-1,0
       0      .1       0  206.11    .045       0  230.56      .1       0
Bank Sta=206.11,230.56
XS Rating Curve= 0 ,0
Exp/Cntr(USF)=0,0
Exp/Cntr=0.3,0.1

Type RM Length L Ch R = 1 ,16159   ,285,282,281.2
XS GIS Cut Line= 2
1662803.25288972469983.133202615 1662431.4085085470162.486761498
#Sta/Elev= 30
       0 1099.37    20.8 1094.11      48 1086.33    71.4 1075.62      90 1066.45
    98.4  1061.4   105.8 1058.34   122.8 1047.29   135.3 1037.07   144.7 1030.25
   152.5  1023.1   155.6 1019.15   159.2  1013.3   162.9 1009.04     182  996.62
   184.7   995.6   195.6  995.39   210.2  995.66214.7331996.6199   221.1  998.75
   232.1 1001.25   250.3 1001.42   297.6 1000.45   312.3 1001.51   323.1 1003.87
   330.4 1006.91   359.6 1022.41   383.5 1038.12   403.1 1053.72   412.8 1057.87
#Mann= 3 ,-1,0
       0      .1       0     182    .045       0214.7331      .1       0
#XS Ineff= 2 , 0
                          248.73         1031.32
Permanent Ineff=
       F       F
Bank Sta=182,214.7331
XS Rating Curve= 0 ,0
Exp/Cntr(USF)=0,0
Exp/Cntr=0.3,0.1

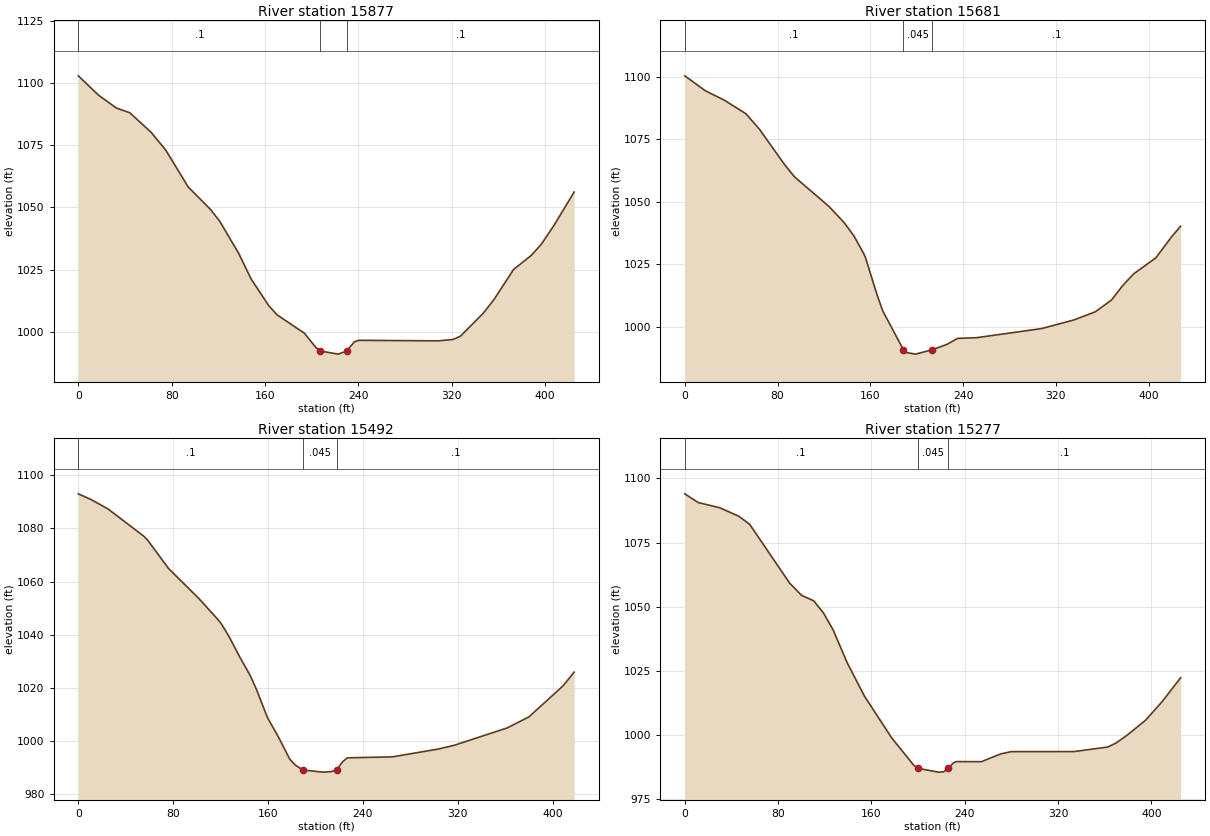
Type RM Length L Ch R = 1 ,15877   ,198.6,196.4,192.4
XS GIS Cut Line= 6
1662658.06431551469718.6953748321662583.54412334469764.553878918
1662519.66957918 469803.861215011662434.50373901469856.270559013
1662370.62919484 469895.577895091662297.78550851 469944.16047509
#Sta/Elev= 30
       0 1102.83    17.2 1095.12    32.6 1089.91    44.1 1088.02    62.3 1080.22
      75    1073    94.2 1058.23   113.5 1049.13   121.2 1044.48   137.4 1031.66
   148.1 1021.36   163.1  1010.7   170.3 1006.94   193.8  999.56   203.7  993.79
  207.48992.4072   222.8  991.15  230.01992.4081   236.8  996.15   240.6  996.69
   308.6  996.48   321.5  997.05   327.7  998.39   347.1 1007.54   356.2 1012.95
   373.2 1025.15   388.2 1030.71   396.9 1035.22   407.9 1042.87   425.1 1056.21
#Mann= 3 ,-1,0
       0      .1       0  207.48    .045       0  230.01      .1       0
Bank Sta=207.48,230.01
XS Rating Curve= 0 ,0
Exp/Cntr(USF)=0,0
Exp/Cntr=0.3,0.1

Type RM Length L Ch R = 1 ,15681   ,188.7,189,188.7
XS GIS Cut Line= 6
 1662482.1889877469528.9770888961662423.54573229469596.156416488
1662375.10849321 469654.574278651662306.12339495469727.010485483
1662253.09036455469780.0435159031662191.21844104469841.915439394
#Sta/Elev= 30
       0 1100.46    17.7 1094.49    33.9 1090.76    52.6 1085.33    64.4 1079.09
    86.1 1064.91    94.7 1060.01   124.6 1048.09   137.4 1041.75   145.9 1036.38
   154.4 1029.26   155.9 1027.64   166.1 1012.42   170.8 1006.35  188.54990.8775
     190  989.84     199  989.12  213.49 990.878   226.2  993.04   235.3  995.42
   251.7   995.7   307.7  999.34   335.5 1002.78   354.1 1006.07     368 1010.78
   377.8 1016.62   387.1 1021.23   406.2 1027.62   420.1 1036.24   427.6 1040.29
#Mann= 3 ,-1,0
       0      .1       0  188.54    .045       0  213.49      .1       0
Bank Sta=188.54,213.49
XS Rating Curve= 0 ,0
Exp/Cntr(USF)=0,0
Exp/Cntr=0.3,0.1

Type RM Length L Ch R = 1 ,15492   ,216.1,214.7,213.3
XS GIS Cut Line= 2
1662348.90538658469411.6182384751662062.89010823469716.701202046
#Sta/Elev= 30
       0 1093.05    10.7 1090.91    25.1 1087.34    55.2 1077.11    58.6 1075.54
    76.1 1064.94   101.6 1053.67   117.9 1045.65     121 1043.83   127.1 1039.34
   136.4 1031.41     145 1024.63   150.4 1019.23   159.6 1008.74     169 1001.33
   178.2  993.25   182.8  991.01  189.16 989.104   206.1  988.27     213  988.44
   217.8 989.105   222.8  992.13   226.9  993.65   264.9  994.02   303.3  996.93
   317.3  998.41   361.6  1004.9     380 1009.05   408.8 1020.73   418.2 1025.92
#Mann= 3 ,-1,0
       0      .1       0  189.16    .045       0   217.8      .1       0
Bank Sta=189.16,217.8
XS Rating Curve= 0 ,0
Exp/Cntr(USF)=0,0
Exp/Cntr=0.3,0.1

Type RM Length L Ch R = 1 ,15277   ,298,300,301.5
XS GIS Cut Line= 6
1662177.62892467469250.0946060121662124.54504134469319.652865842
1662079.04480426469379.2744657551662018.37760276469458.769713596
1661972.87703758469518.3913135081661919.79348233469587.949573338
#Sta/Elev= 30
       0 1093.96    11.5 1090.57      30 1088.53    46.4 1085.22    55.7 1082.04
    89.9 1059.17   100.2 1054.39   110.5 1052.31   118.9 1047.54   127.1 1041.02
   139.4 1027.99     154 1015.18   177.4  998.89   196.2  988.31  199.57987.1119
   217.2  985.59     222  985.73  225.96987.1116   230.2  989.18   232.6  989.69
   254.3  989.66   270.5  992.64   279.8  993.57   333.4  993.58   362.4  995.35
   369.4  996.86   378.8  999.86   395.1 1005.86   409.2 1013.07     425 1022.33
#Mann= 3 ,-1,0
       0      .1       0  199.57    .045       0  225.96      .1       0
Bank Sta=199.57,225.96
XS Rating Curve= 0 ,0
Exp/Cntr(USF)=0,0
Exp/Cntr=0.3,0.1