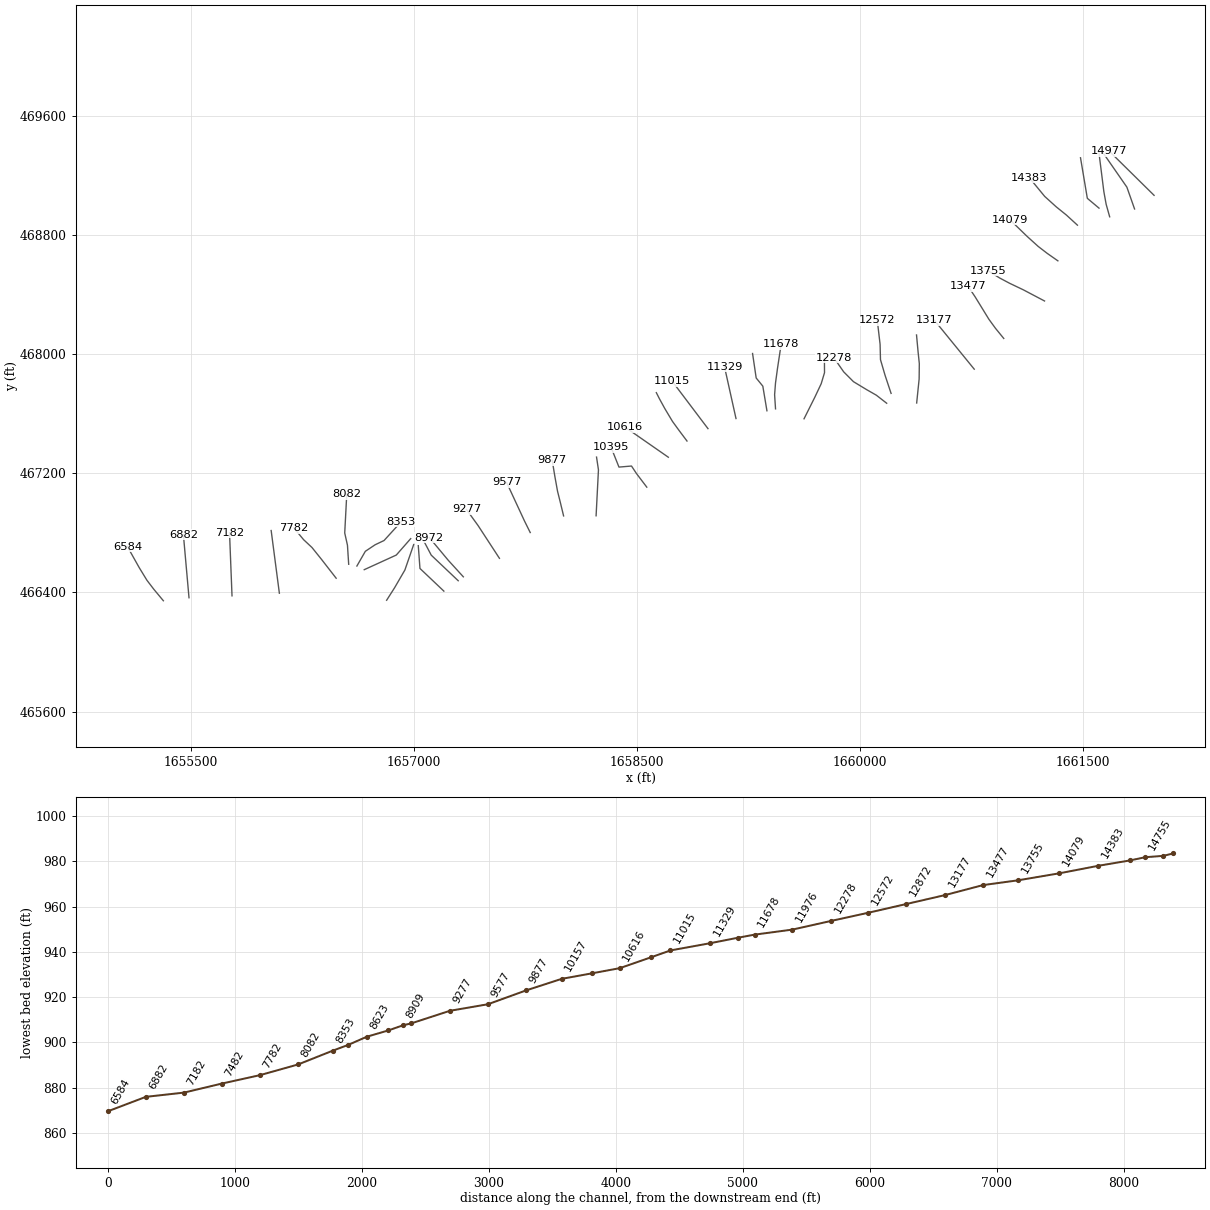
HEC-RAS study BigRnI.prj: BigRnI

--- BigRnI.g01 (geometry) --- (continued)

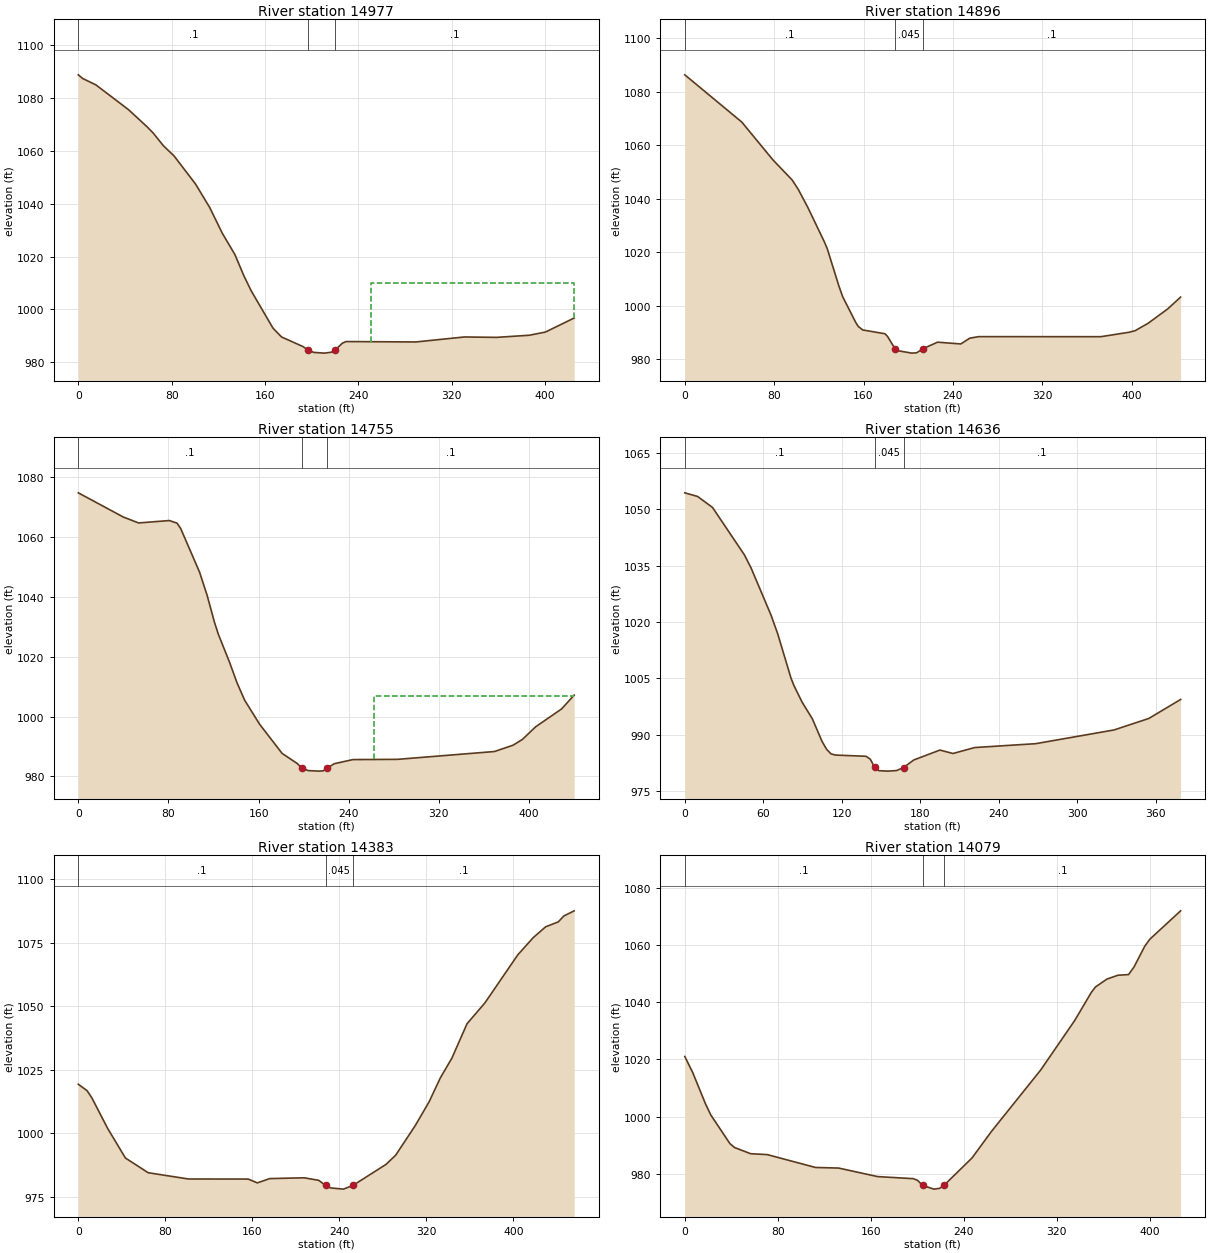
Type RM Length L Ch R = 1 ,14977   ,83.2,81.4,78.6
XS GIS Cut Line= 6
1661976.83109793469069.8886015861661914.50970025469131.307113916
1661861.09117192469183.9516936691661789.86624876469254.144466668
1661736.44772042469306.7890464221661674.12599467469368.207886845
#Sta/Elev= 30
       0 1088.88     3.8 1087.48    15.1 1085.06      43 1075.69      59 1069.16
    64.1 1066.86    72.9 1062.02    82.1 1058.13   100.5 1047.49   112.6 1038.62
   123.5 1028.78   134.2  1020.8   141.9 1012.75   148.2 1007.03   166.9  992.88
   174.2  989.56   192.6  985.92  197.06984.5562   201.8  983.71     211  983.44
     217   983.8  220.01984.5585   226.3   987.2   229.5  987.82   289.3  987.67
   330.8  989.56   358.6  989.41   386.6  990.22   400.3  991.41     425  996.74
#Mann= 3 ,-1,0
       0      .1       0  197.06    .045       0  220.01      .1       0
#XS Ineff= 2 , 0
                          250.71         1009.85
Permanent Ineff=
       F       F
Bank Sta=197.06,220.01
XS Rating Curve= 0 ,0
Exp/Cntr(USF)=0,0
Exp/Cntr=0.3,0.1

Type RM Length L Ch R = 1 ,14896   ,145.6,140.8,133.6
XS GIS Cut Line= 3
1661845.67713983468978.2022533941661793.96786562469124.989870487
1661629.66581695 469361.85170716
#Sta/Elev= 30
       0 1086.32      51 1068.68    78.8 1054.59    96.2    1047   101.6 1043.52
   110.1 1036.83   124.8 1024.05   127.5 1021.43   137.9  1007.5   141.4 1003.39
     153  993.84   155.3  992.32   159.3  991.01   179.3  989.58   181.6  988.53
  188.16984.0328   191.2  983.22   203.2  982.35   207.5  982.46  213.39984.0335
   226.3  986.44   247.1  985.78   255.1  987.93   263.1  988.51   372.5  988.49
   397.8  990.15   403.2  990.74   414.8   993.5   432.4  998.89   443.9 1003.29
#Mann= 3 ,-1,0
       0      .1       0  188.16    .045       0  213.39      .1       0
Bank Sta=188.16,213.39
XS Rating Curve= 0 ,0
Exp/Cntr(USF)=0,0
Exp/Cntr=0.3,0.1

Type RM Length L Ch R = 1 ,14755   ,118.7,119,119.7
XS GIS Cut Line= 4
1661678.28132738468925.5767169541661654.61864504469009.816377858
1661639.34000052469093.6979017471661605.88222219469358.927192779
#Sta/Elev= 30
       0 1074.82    39.9 1066.73    53.5 1064.75    80.8 1065.55    87.6 1064.69
    90.9 1062.85   107.6 1048.31   114.3 1040.57   120.9 1031.47   124.3 1027.51
   134.3 1018.09   140.9 1011.26   147.6  1005.5   160.9  997.45   180.9  987.68
   194.1  984.36  198.37982.8248     204  981.94   213.9  981.76   217.3  981.85
  221.11982.8246   227.2  984.24   243.7  985.62   283.4   985.7   369.4  988.32
   385.9  990.43   394.2  992.37   405.9  996.58   428.9 1002.54   440.1 1007.18
#Mann= 3 ,-1,0
       0      .1       0  198.37    .045       0  221.11      .1       0
#XS Ineff= 2 , 0
                          262.86          1006.9
Permanent Ineff=
       F       F
Bank Sta=198.37,221.11
XS Rating Curve= 0 ,0
Exp/Cntr(USF)=0,0
Exp/Cntr=0.3,0.1

Type RM Length L Ch R = 1 ,14636   ,242.6,252.8,258.9
XS GIS Cut Line= 3
1661606.51173266468983.918322331 1661528.1138008469049.805945913
1661482.24267046469322.530666308
#Sta/Elev= 30
       0 1054.37     9.8  1053.4    21.2 1050.48    45.5  1037.9    50.6 1034.44
    65.9 1021.86      71  1016.9    81.2 1005.07    83.5 1003.05    89.7  998.68
    97.5  994.27   104.9  988.26   108.5   986.1   111.8  984.94   115.2  984.62
   138.5   984.3   141.8  983.53   145.1  981.35   148.4  980.47   155.1  980.35
   161.9   980.5  167.25981.3047     175  983.31     195  985.95     205  985.04
   221.6  986.62   268.2  987.65   328.1   991.3   354.7  994.36     379  999.41
#Mann= 3 ,-1,0
       0      .1       0   145.1    .045       0  167.25      .1       0
Bank Sta=145.1,167.25
XS Rating Curve= 0 ,0
Exp/Cntr(USF)=0,0
Exp/Cntr=0.3,0.1

Type RM Length L Ch R = 1 ,14383   ,301.1,304.3,303.8
XS GIS Cut Line= 6
1661461.65397868468869.3030447511661387.51731592468937.292082012
1661319.59061451 468992.078061671661241.27154543469062.911909506
1661193.64893726469120.8346939241661138.10180426469188.400175586
#Sta/Elev= 30
       0 1019.24       8 1016.73    12.4 1013.92      27 1001.82    43.3   990.2
    64.2  984.41   101.3  981.94   156.2  981.91   164.6  980.41     176   982.1
   207.7  982.41     221  981.42  227.35979.4186   231.8  978.43   243.8  977.95
  252.55979.4212   282.9  987.68   291.8  991.31   309.8 1002.97   322.5  1012.3
   332.8  1021.7   343.5 1029.53   357.4 1043.07   373.8 1051.25   404.1  1070.2
   418.2 1076.94   429.7 1081.23   441.3 1083.17   446.4 1085.47   455.9 1087.52
#Mann= 3 ,-1,0
       0      .1       0  227.35    .045       0  252.55      .1       0
Bank Sta=227.35,252.55
XS Rating Curve= 0 ,0
Exp/Cntr(USF)=0,0
Exp/Cntr=0.3,0.1

Type RM Length L Ch R = 1 ,14079   ,321,323.9,325.2
XS GIS Cut Line= 6
1661330.12372993468629.5794428441661257.70819233468680.309000179
1661197.90155342468726.3633700011661123.71075693468793.499718666
1661069.84209825468845.6839975121661006.99576725  468906.5657655
#Sta/Elev= 30
       0 1020.98     6.8 1015.39    17.9 1004.36    22.4 1000.54    38.8  990.57
    42.8  989.19    56.7  987.03    70.9  986.72   112.4  982.23   132.4  982.01
   165.8  979.04   196.6  978.31   200.2  977.73  204.62975.9434   214.3  974.66
   219.2  974.94  222.86 975.942   247.1  985.56   263.7  994.77   306.2  1016.3
   335.3  1033.5   349.7 1043.37   353.3 1045.28   363.1 1048.02   372.6 1049.37
   381.7 1049.59   386.4 1052.24   395.6 1059.47     400 1061.94   426.5 1071.86
#Mann= 3 ,-1,0
       0      .1       0  204.62    .045       0  222.86      .1       0
Bank Sta=204.62,222.86
XS Rating Curve= 0 ,0
Exp/Cntr(USF)=0,0
Exp/Cntr=0.3,0.1

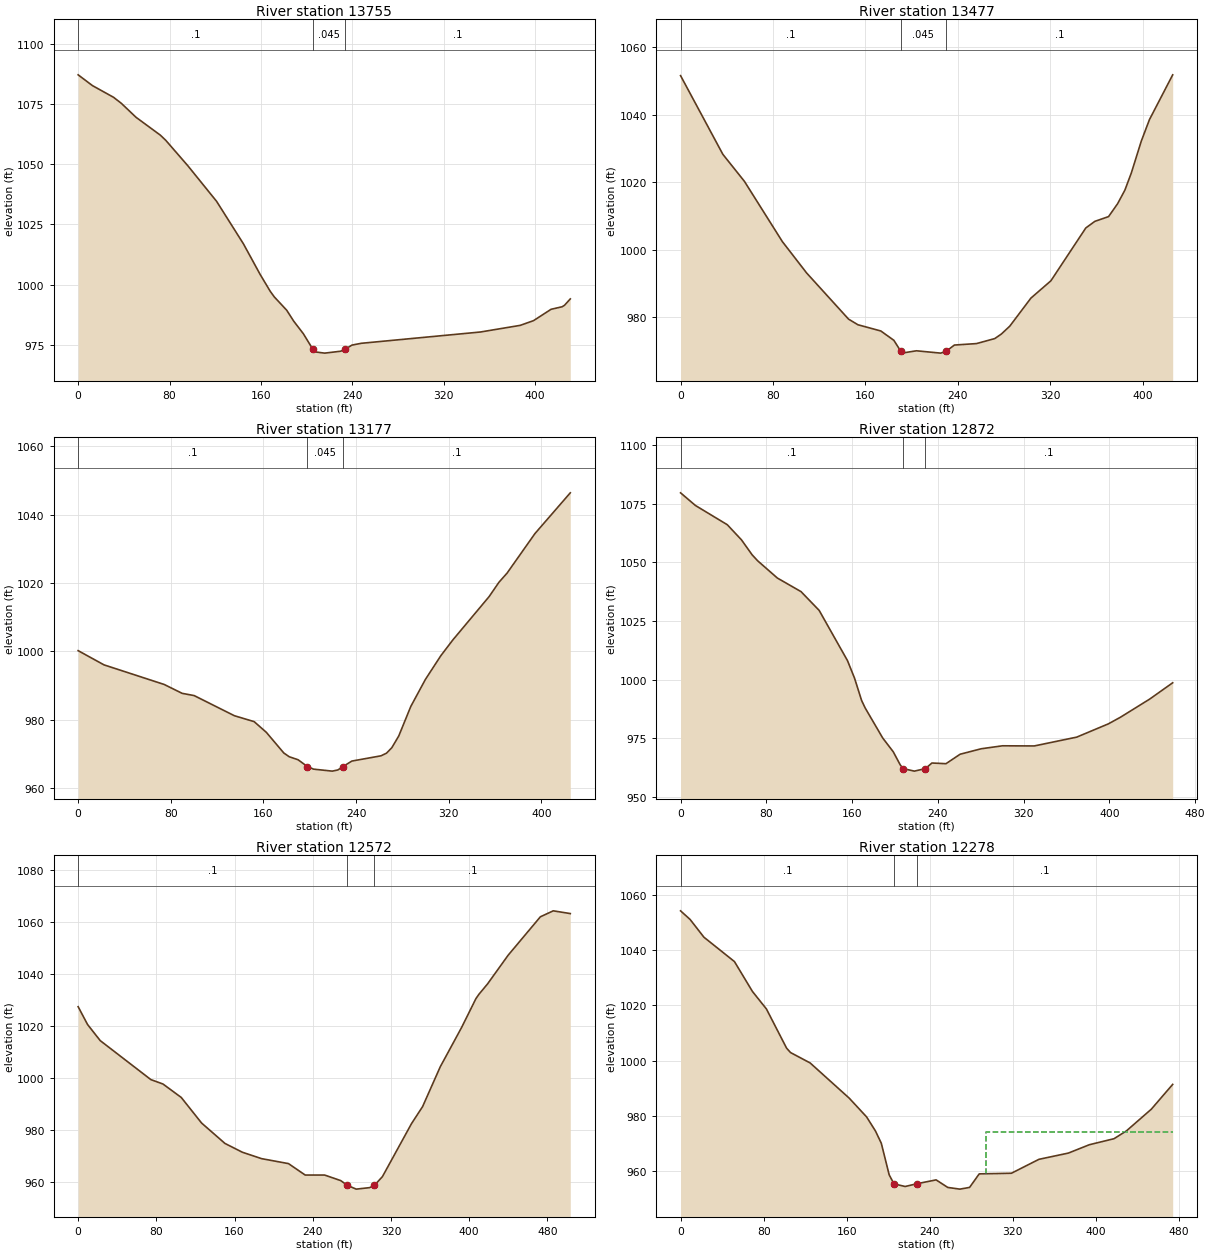
Type RM Length L Ch R = 1 ,13755   ,285,277.8,266.8
XS GIS Cut Line= 6
 1661240.4363116468359.6317236451661163.00602026468400.384266812
1661096.63673043468435.3149712411661006.30029693468478.384766984
1660938.33816251468514.4332513241660860.88293685468562.766816068
#Sta/Elev= 30
       0 1087.11    12.5 1082.64      31 1077.78    37.8 1075.28    50.7 1069.47
    71.9 1062.09    76.7 1059.92    96.1 1049.32   121.2 1034.59   144.7 1016.94
   159.2 1004.35   168.1  997.28   171.7  994.92   182.6  989.37   188.7  984.85
   197.1  979.66  205.46973.1766   208.4  972.03   215.8  971.58   229.8  972.37
  233.68 973.176   239.7  974.91   247.8  975.66   352.2  980.35     387  983.11
   398.6  985.06     414  989.78   423.6  990.82   425.7  991.42   430.8  994.09
#Mann= 3 ,-1,0
       0      .1       0  205.46    .045       0  233.68      .1       0
Bank Sta=205.46,233.68
XS Rating Curve= 0 ,0
Exp/Cntr(USF)=0,0
Exp/Cntr=0.3,0.1

Type RM Length L Ch R = 1 ,13477   ,294.7,300,301.3
XS GIS Cut Line= 6
1660966.21599318468107.8872447611660910.50547467468176.146950752
 1660866.2765605468236.9995193331660813.95022158468322.216540501
1660774.70587751468386.1294704231660726.16955726468459.005637005
#Sta/Elev= 30
       0  1051.5    36.6 1028.24    55.3 1020.23    88.1 1002.43   109.1  993.15
   145.4   979.5   153.5  977.84   173.3     976   184.6  973.24   190.4   970.1
   192.5  969.51   204.1  970.14   225.1  969.45   229.9     970     237  971.84
   256.1  972.27   271.9  973.75   277.6  975.09   284.9  977.42   303.2  985.72
   320.5  990.84   350.7 1006.46   358.5 1008.41   370.4 1009.82   378.2 1013.62
   384.5 1017.63   390.1 1022.72   398.7 1032.12   405.8 1038.51   425.9 1051.74
#Mann= 3 ,-1,0
       0      .1       0   190.4    .045       0   229.9      .1       0
Bank Sta=190.4,229.9
XS Rating Curve= 0 ,0
Exp/Cntr(USF)=0,0
Exp/Cntr=0.3,0.1

Type RM Length L Ch R = 1 ,13177   ,307,304.6,292
XS GIS Cut Line= 6
1660767.78167875467901.3699412491660712.52489951467969.214949921
1660665.16213334468027.3677207531660602.01134101468104.904967248
1660554.64857484468163.0577380961660499.39179559468230.903074846
#Sta/Elev= 30
       0 1000.23    22.3  996.08    74.3  990.35    89.8  987.76   100.2   987.1
   134.9  981.22     152  979.49   162.5  976.37   177.6  970.33   182.3  969.23
   189.9  968.36  197.98 966.372   203.3  965.61   219.5  965.03   224.3  965.37
  228.68966.3705   236.4  967.97   261.6  969.51   266.3  970.28   270.9  971.88
   276.9  975.32   287.3  983.95   299.9  991.83   313.2  998.75   323.6 1003.37
   354.9 1016.02   363.4 1020.21   370.4 1022.88   394.5 1034.44     425 1046.34
#Mann= 3 ,-1,0
       0      .1       0  197.98    .045       0  228.68      .1       0
Bank Sta=197.98,228.68
XS Rating Curve= 0 ,0
Exp/Cntr(USF)=0,0
Exp/Cntr=0.3,0.1

Type RM Length L Ch R = 1 ,12872   ,293.7,300,297.7
XS GIS Cut Line= 6
1660380.86775443467673.892377838   1660389.79523467760.935510844
1660397.44744568467835.5442855061660398.62690526 467938.73075892
  1660389.747986468024.1285540011660379.85988243468131.243497252
#Sta/Elev= 30
       0 1079.66    13.9 1074.26    43.6 1066.07    56.8 1059.64    66.7 1053.29
    71.9 1050.71    90.3 1043.36   112.4 1037.56   129.3 1029.57   155.7 1008.19
   162.3 1000.71   168.9  991.18   172.2  988.02   188.6  975.19   198.4  969.34
     205   963.7  207.71962.1644   218.1  961.09   228.4962.1633   234.5  964.55
   247.6  964.26   260.8  968.29   280.5  970.62   300.3  971.88     330  971.82
   369.6  975.58   399.2  981.25   410.5  984.09   437.6  991.77   459.1  998.73
#Mann= 3 ,-1,0
       0      .1       0  207.71    .045       0   228.4      .1       0
Bank Sta=207.71,228.4
XS Rating Curve= 0 ,0
Exp/Cntr(USF)=0,0
Exp/Cntr=0.3,0.1

Type RM Length L Ch R = 1 ,12572   ,276.9,294.1,304.6
XS GIS Cut Line= 6
1660208.82380718 467738.509046511660168.73760125467858.976325259
1660137.57427776467965.3022280931660134.95157959468068.537585929
1660126.18847376468143.0239855051660115.96506901468229.924730346
#Sta/Elev= 30
       0 1027.49     9.6 1020.65    22.6 1014.42    74.4  999.41    86.8  997.71
   105.5  992.53   126.3  982.68   150.2  974.83     168  971.44   187.8  968.96
   215.2  967.06   232.3  962.65   252.2  962.65   268.6  960.52  275.47958.6783
   284.5  957.23   298.1   957.8  303.07958.6807   311.3  962.04     341  982.42
   352.4  989.01   370.5 1004.36   392.3 1019.48     407 1030.62     410 1032.25
   418.9 1036.28   439.9  1047.3   472.9 1062.11   486.1 1064.41   503.5 1063.35
#Mann= 3 ,-1,0
       0      .1       0  275.47    .045       0  303.07      .1       0
Bank Sta=275.47,303.07
XS Rating Curve= 0 ,0
Exp/Cntr(USF)=0,0
Exp/Cntr=0.3,0.1

Type RM Length L Ch R = 1 ,12278   ,314.5,302.4,279.7
XS GIS Cut Line= 6
1660179.22773775 467672.259507091660109.54513434467726.477246419
1660044.42682625467763.6874738341659956.15206842467817.156855091
1659890.19419509467883.3187962621659825.13658242467976.929501429
#Sta/Elev= 30
       0 1054.17     9.2 1051.05    22.5 1044.64    51.9 1035.83    69.2 1025.05
    82.7  1018.7   102.1 1004.55   105.9 1002.96   124.8   999.2   162.5  986.45
   179.2  979.68   187.7   974.6   193.3  970.19   200.9  958.77   205.5  955.52
   216.3  954.56   227.8  955.58   246.1  956.95   257.3  954.22     269  953.61
   278.3  954.23   287.6  959.12   318.6  959.35   345.1  964.38   373.4  966.63
   393.7  969.66   417.4  971.83   429.4  974.67   453.3  982.49   473.9  991.46
#Mann= 3 ,-1,0
       0      .1       0   205.5    .045       0   227.8      .1       0
#XS Ineff= 2 , 0
                          294.23          974.42
Permanent Ineff=
       F       F
Bank Sta=205.5,227.8
XS Rating Curve= 0 ,0
Exp/Cntr(USF)=0,0
Exp/Cntr=0.3,0.1

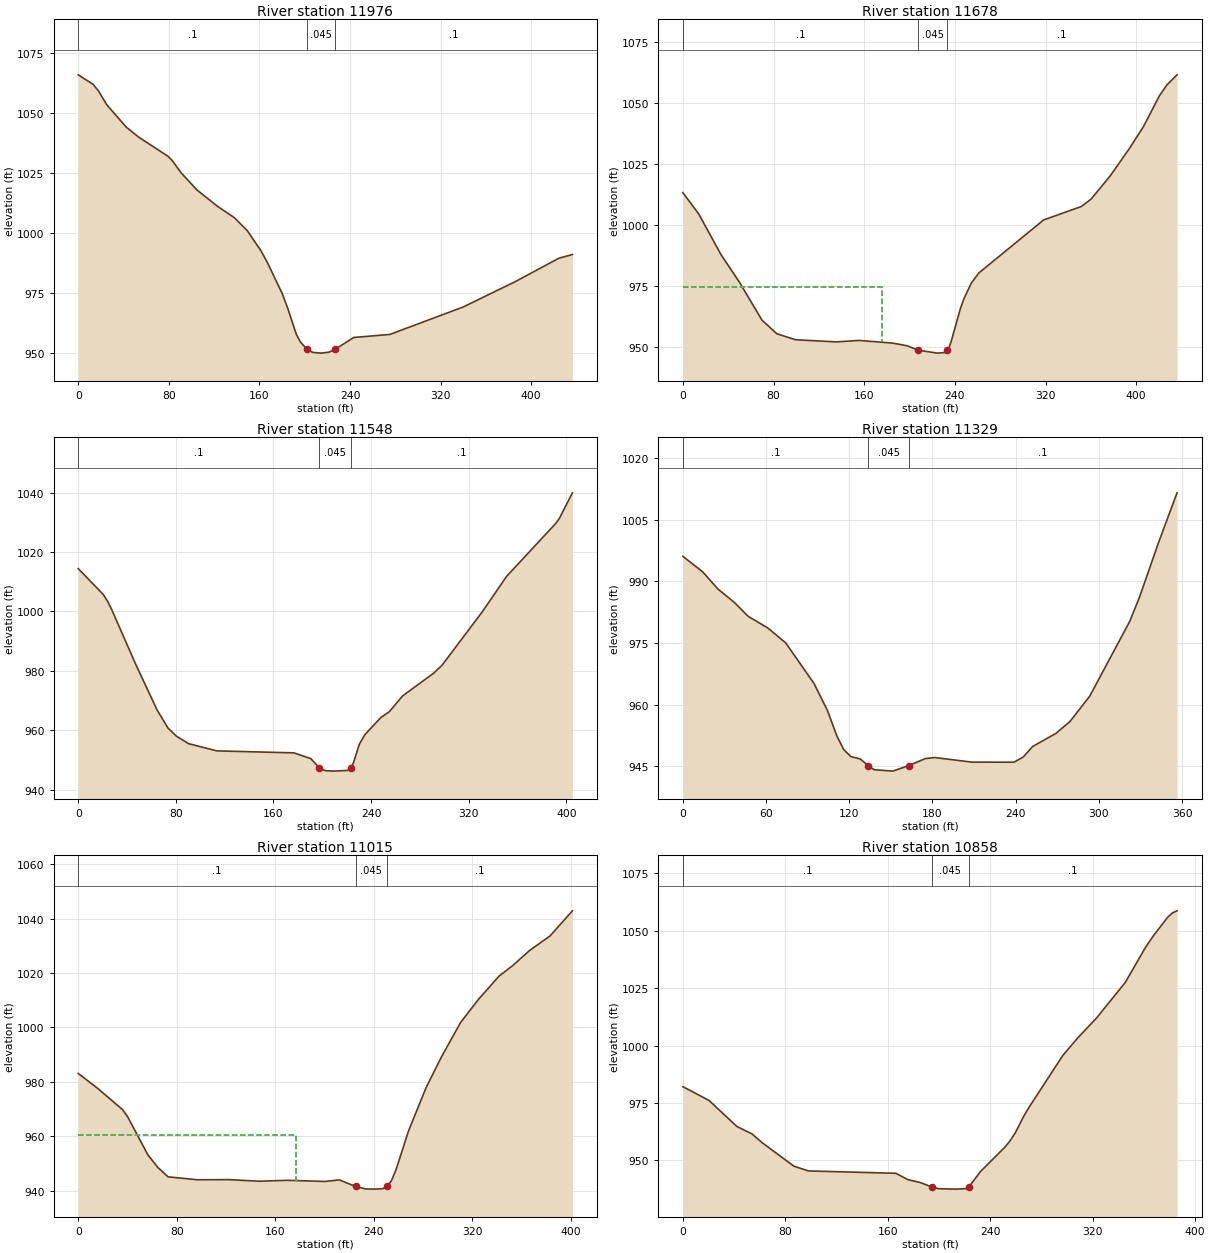
Type RM Length L Ch R = 1 ,11976   ,293.4,298.1,301.3
XS GIS Cut Line= 6
1659623.70916376467567.7508578451659662.84097525467646.012512341
1659696.38257484467713.0943991691659739.06687267467803.555832416
1659761.35980709467877.7738598441659760.71938843467974.157197252
#Sta/Elev= 30
       0 1066.03    13.1 1062.06    17.8 1059.36    25.1 1053.58    42.4  1044.2
    53.4    1040    79.1 1032.07    82.8 1030.36    91.1 1024.98   104.8 1017.96
   123.1 1011.08   137.8  1006.4   149.2 1001.01   161.4  992.54   167.1  987.57
     180  974.81   185.2  968.29   192.5  957.78   196.1  954.55  201.77 951.482
     207  950.14   214.3  949.81   221.5  950.22  227.18 951.482   243.3  956.35
   275.2  957.61     340  969.09   386.2  979.73   424.4  989.43   436.4     991
#Mann= 3 ,-1,0
       0      .1       0  201.77    .045       0  227.18      .1       0
Bank Sta=201.77,227.18
XS Rating Curve= 0 ,0
Exp/Cntr(USF)=0,0
Exp/Cntr=0.3,0.1

Type RM Length L Ch R = 1 ,11678   ,116,130.1,137.3
XS GIS Cut Line= 6
1659432.05305101467634.5010524241659425.84538625467729.520219341
1659431.82076801 467807.596506761659445.29941559467906.695389926
1659456.53495742467980.8491130021659469.64319892468067.361735255
#Sta/Elev= 30
       0 1013.24    13.9  1004.6    33.6  987.93    50.1  976.45    69.8  961.07
    82.9  955.52    99.4  953.06   135.6  952.18   155.3  952.78     185  951.69
   198.2  950.57  207.32 948.792   224.7  947.58   231.3  947.85  233.12948.7898
   234.7  949.56     237   952.8   244.6  965.43   247.9   969.8   254.5  976.25
   261.1  980.38   318.3 1002.09   351.5 1007.57   360.2 1010.62   377.3 1020.28
   393.9 1031.28   406.3 1040.23   420.4 1052.84     427 1057.31     436 1061.47
#Mann= 3 ,-1,0
       0      .1       0  207.32    .045       0  233.12      .1       0
#XS Ineff= 2 , 0
          175.81  974.64
Permanent Ineff=
       F       F
Bank Sta=207.32,233.12
XS Rating Curve= 0 ,0
Exp/Cntr(USF)=0,0
Exp/Cntr=0.3,0.1

Type RM Length L Ch R = 1 ,11548   ,223.2,218.3,210
XS GIS Cut Line= 4
1659374.26406633467621.6625140621659346.56624381 467787.17389254
1659301.97950511467841.8939809351659277.65946583468006.729802766
#Sta/Elev= 30
       0 1014.43    20.4 1005.77    23.7  1003.7    27.1 1000.95      47   982.3
    64.6  966.84    73.6  960.72    80.3  958.06    90.3   955.5   113.6  953.05
   176.7  952.38   190.6  950.46   197.6  947.34   202.3  946.39   209.3  946.23
     221  946.48   223.3  947.39   225.5  948.95   230.3  955.22   234.9  958.52
   248.1  964.31     255  966.27   265.9  971.58   291.5  979.29   298.1  981.87
   331.3  999.98   351.2 1011.89     391  1029.5   394.3 1031.32     405 1039.96
#Mann= 3 ,-1,0
       0      .1       0   197.6    .045       0   223.3      .1       0
Bank Sta=197.6,223.3
XS Rating Curve= 0 ,0
Exp/Cntr(USF)=0,0
Exp/Cntr=0.3,0.1

Type RM Length L Ch R = 1 ,11329   ,305.4,314.2,315.2
XS GIS Cut Line= 2
1659166.27248992 467569.481426581659088.97138809467917.423386842
#Sta/Elev= 30
       0  996.12    14.3  992.34    25.3  988.15    37.1  984.91    47.2  981.48
      61  978.74    74.1  975.07    94.6  965.15   104.3  958.56     111  952.42
     116  949.07   121.1  947.36   127.9  946.78  133.64945.1658   137.9  944.16
   151.4  943.81  162.97945.1639   174.9  946.87   181.6  947.12   208.5     946
   238.8  945.98   245.5  947.25   252.2   949.8     269  952.99   279.1  955.87
   293.4  962.05   322.3  980.29   329.5  986.33   342.9  999.32   356.4 1011.59
#Mann= 3 ,-1,0
       0      .1       0  133.64    .045       0  162.97      .1       0
Bank Sta=133.64,162.97
XS Rating Curve= 0 ,0
Exp/Cntr(USF)=0,0
Exp/Cntr=0.3,0.1

Type RM Length L Ch R = 1 ,11015   ,158.4,157.4,155.1
XS GIS Cut Line= 2
 1658977.8830222467501.5540071641658736.20659263467821.718855642
#Sta/Elev= 30
       0  983.12    15.4  977.77      36  969.81    40.1  967.19    56.5  953.23
    64.7  948.54    72.9  945.13    96.5  944.05   122.3   944.1   146.9  943.51
   169.8  943.85   200.4  943.43   211.9  944.01  225.16941.5796     233  940.69
     240  940.61   247.1  940.76  250.62941.5816   254.1  943.61   257.9   947.7
   268.1  962.01   282.2  977.75   294.9  989.26   310.3 1001.81   325.2 1010.51
   341.6 1018.89   352.5 1022.69   366.5 1028.35   382.9 1033.61   401.1 1042.86
#Mann= 3 ,-1,0
       0      .1       0  225.16    .045       0  250.62      .1       0
#XS Ineff= 2 , 0
          176.65  960.41
Permanent Ineff=
       F       F
Bank Sta=225.16,250.62
XS Rating Curve= 0 ,0
Exp/Cntr(USF)=0,0
Exp/Cntr=0.3,0.1

Type RM Length L Ch R = 1 ,10858   ,234.2,242.2,245.8
XS GIS Cut Line= 6
1658836.81063237467418.2799573381658783.75562037467488.978634833
1658739.29606363467550.1346805081658687.98645496467636.046254082
1658651.92419113467701.8076055041658630.70162634467743.499717495
#Sta/Elev= 30
       0  982.13    20.4  976.13    42.2  964.78    53.9  961.57    62.1  957.65
    86.7   947.5    98.1  945.42   166.3   944.4   175.8  941.61   185.4  940.38
  194.56938.4105   199.7  937.68   213.4   937.5   221.1  937.71  223.25938.4114
   232.6  945.27   251.7  955.92   255.5  958.54   259.6  962.02   266.5  969.57
   270.6  973.38   296.8  995.78     308 1003.14     323    1012   345.4 1027.45
   361.2  1042.7   367.4  1047.8   378.5 1055.86   382.2 1057.74   385.9  1058.7
#Mann= 3 ,-1,0
       0      .1       0  194.56    .045       0  223.25      .1       0
Bank Sta=194.56,223.25
XS Rating Curve= 0 ,0
Exp/Cntr(USF)=0,0
Exp/Cntr=0.3,0.1

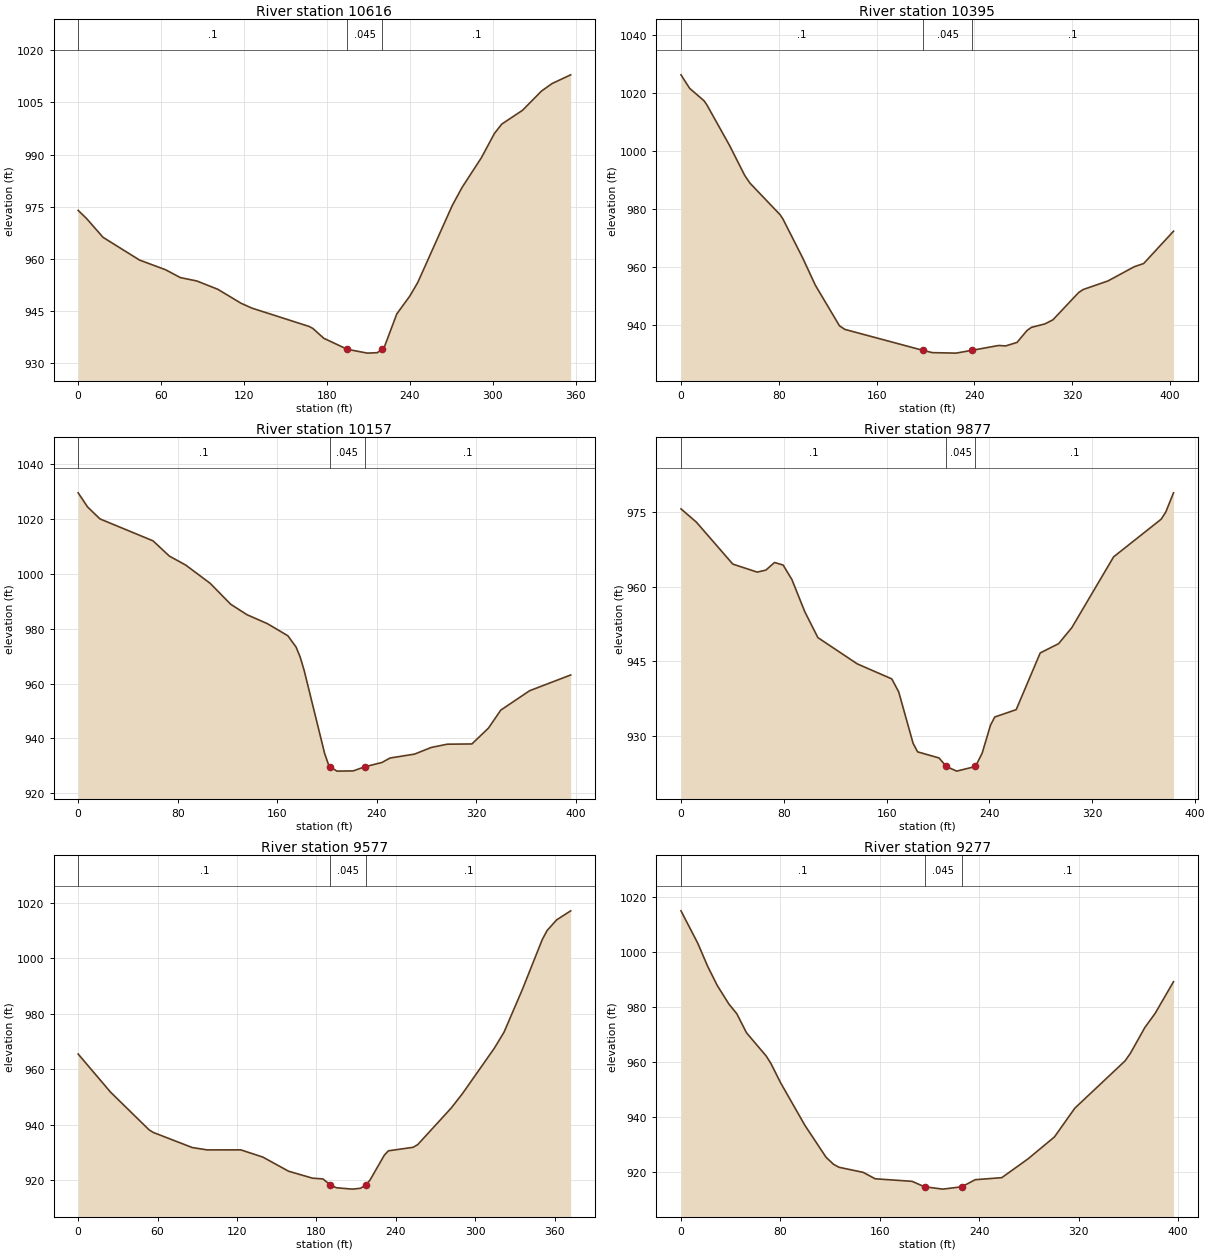
Type RM Length L Ch R = 1 ,10616   ,205.1,220.9,231.1
XS GIS Cut Line= 2
1658711.42790667467309.3271295161658418.68669304467512.828144122
#Sta/Elev= 30
       0  973.91       6   971.6      18  966.15    44.4   959.6    63.3   956.8
      74  954.54    85.9  953.57     101  951.19   117.9  947.15   125.9  945.73
     167  940.49   169.8  939.92   177.8  937.06  194.78933.8824   209.4  932.78
   216.5  932.91  220.13933.8837   221.8  934.72   230.6  944.06   240.1  949.25
   245.8  953.13   270.7  975.25   277.8  980.47   291.9  989.11   301.3  996.07
   306.6  998.77   321.7 1002.77   335.3 1008.27     343 1010.45   356.5 1012.97
#Mann= 3 ,-1,0
       0      .1       0  194.78    .045       0  220.13      .1       0
Bank Sta=194.78,220.13
XS Rating Curve= 0 ,0
Exp/Cntr(USF)=0,0
Exp/Cntr=0.3,0.1

Type RM Length L Ch R = 1 ,10395   ,265.5,237.3,210.2
XS GIS Cut Line= 6
1658566.57332499467108.1281910541658497.76802134467198.903559094
1658463.84156653467250.1445307571658424.44310289467246.861325454
 1658379.5726304467243.030919266 1658326.6372352467375.729786422
#Sta/Elev= 30
       0 1026.25     7.1 1021.59    18.8 1017.34    21.1 1015.97    39.8 1001.88
    52.1  991.65    56.3  989.03      81  978.13    83.4  976.62    99.7  963.09
   109.8  953.92   129.6  939.89     134  938.65197.6441931.4611   205.6  930.65
   224.9  930.48238.3641931.4763   259.9  933.12   265.4  932.95   274.8  934.16
     283  938.27   286.6  939.35   297.6  940.53   304.2  941.95   325.3  951.37
     329  952.38   349.2  955.32   370.8  960.24   378.4  961.31   402.8  972.44
#Mann= 3 ,-1,0
       0      .1       0197.6441    .045       0238.3641      .1       0
Bank Sta=197.6441,238.3641
XS Rating Curve= 0 ,0
Exp/Cntr(USF)=0,0
Exp/Cntr=0.3,0.1

Type RM Length L Ch R = 1 ,10157   ,277.2,280.4,282.8
XS GIS Cut Line= 3
1658225.81038475466915.7036055031658241.67699295467224.368208844
 1658228.7942716467310.279174825
#Sta/Elev= 30
       0 1029.62     7.6 1024.45    17.5 1020.11    60.2 1012.09    73.3 1006.54
    86.5 1003.24   106.2  996.56   122.6  988.96   135.7  985.14   152.2  981.85
   168.6  977.44   175.2  973.31   178.4  969.76   181.7  964.75   198.1  934.54
   201.4  930.22   202.5  929.62     208  928.05   221.1  928.13  230.32929.6262
   244.1  931.19   250.7  932.83   270.4  934.26   283.8  936.69   296.7  937.88
   316.5  937.97   329.8  943.75   339.7  950.31   362.9   957.4   395.9  963.14
#Mann= 3 ,-1,0
       0      .1       0   202.5    .045       0  230.32      .1       0
Bank Sta=202.5,230.32
XS Rating Curve= 0 ,0
Exp/Cntr(USF)=0,0
Exp/Cntr=0.3,0.1

Type RM Length L Ch R = 1 ,9877    ,296.5,300,302.3
XS GIS Cut Line= 6
 1658007.2586565466914.9024260041657985.58251876467004.907167256
1657966.73544359467080.0362820921657948.89722468467178.614168927
1657936.68136984467252.605162665 1657930.6901703467290.116625073
#Sta/Elev= 30
       0  975.58      12  972.91    40.3   964.5    59.3  962.89      66  963.29
    72.8  964.82    79.5   964.3    86.3  961.39    96.4   954.9   106.5  949.75
   137.1  944.48     164  941.46   169.4  938.85   180.6  928.52   184.1  926.82
   200.8  925.59  206.44923.8834   214.5  922.95  229.11923.8845   234.3  926.54
   240.8  932.16   244.1  933.81   260.8  935.29   279.5  946.67   293.8  948.53
   304.1  951.75   336.6  965.95   373.6  973.51   377.2  974.95   383.2   978.8
#Mann= 3 ,-1,0
       0      .1       0  206.44    .045       0  229.11      .1       0
Bank Sta=206.44,229.11
XS Rating Curve= 0 ,0
Exp/Cntr(USF)=0,0
Exp/Cntr=0.3,0.1

Type RM Length L Ch R = 1 ,9577    ,296,300,299.7
XS GIS Cut Line= 6
1657783.00582418466802.9813899991657744.13943209466881.408070415
1657712.57683118466949.4433674221657670.49325392467040.157096758
1657638.93032493 467108.192393751657624.23724728467139.620460859
#Sta/Elev= 30
       0  965.55    24.4  951.85    53.7  938.17    56.8  937.28    86.2  931.84
    97.5  930.99   122.9  931.01   139.6  928.39     159  923.31   177.1   920.8
     185  920.52  190.66918.3115   195.2  917.34   207.2  916.85   213.3  917.16
  217.45918.3125   220.5  920.08   231.4  929.11   234.4  930.66   253.1  931.92
   256.6  932.89     282  946.13   290.6   951.4   314.5  967.65   321.8  973.39
   335.7  988.83   350.7 1006.79   354.4 1010.09   361.6 1013.92   372.2 1017.17
#Mann= 3 ,-1,0
       0      .1       0  190.66    .045       0  217.45      .1       0
Bank Sta=190.66,217.45
XS Rating Curve= 0 ,0
Exp/Cntr(USF)=0,0
Exp/Cntr=0.3,0.1

Type RM Length L Ch R = 1 ,9277    ,303.4,305.3,306.1
XS GIS Cut Line= 6
1657576.01017517466629.8327861731657528.21171434466703.123650089
1657487.24165192466765.944390595 1657432.6141365466849.704721749
1657388.63358143466910.5622115881657354.33513742466958.258375104
#Sta/Elev= 30
       0 1015.04    13.5 1003.27    21.3  995.05    29.2  987.91    38.6  981.15
    44.9  977.68    52.7  970.75    68.5  962.34    72.3  959.64    80.1  952.63
    99.7  937.13   116.7  925.55   122.7  922.98   127.1  921.89   146.7  920.03
   156.2  917.71   185.9  916.78  195.97914.8098   210.7  913.95  225.91914.8106
   236.8  917.38   258.1  918.11   279.3  924.96   300.5  932.91   316.9  943.36
   357.3  960.52   361.6  963.28   373.3   972.7   381.6  977.85   396.3   989.3
#Mann= 3 ,-1,0
       0      .1       0  195.97    .045       0  225.91      .1       0
Bank Sta=195.97,225.91
XS Rating Curve= 0 ,0
Exp/Cntr(USF)=0,0
Exp/Cntr=0.3,0.1

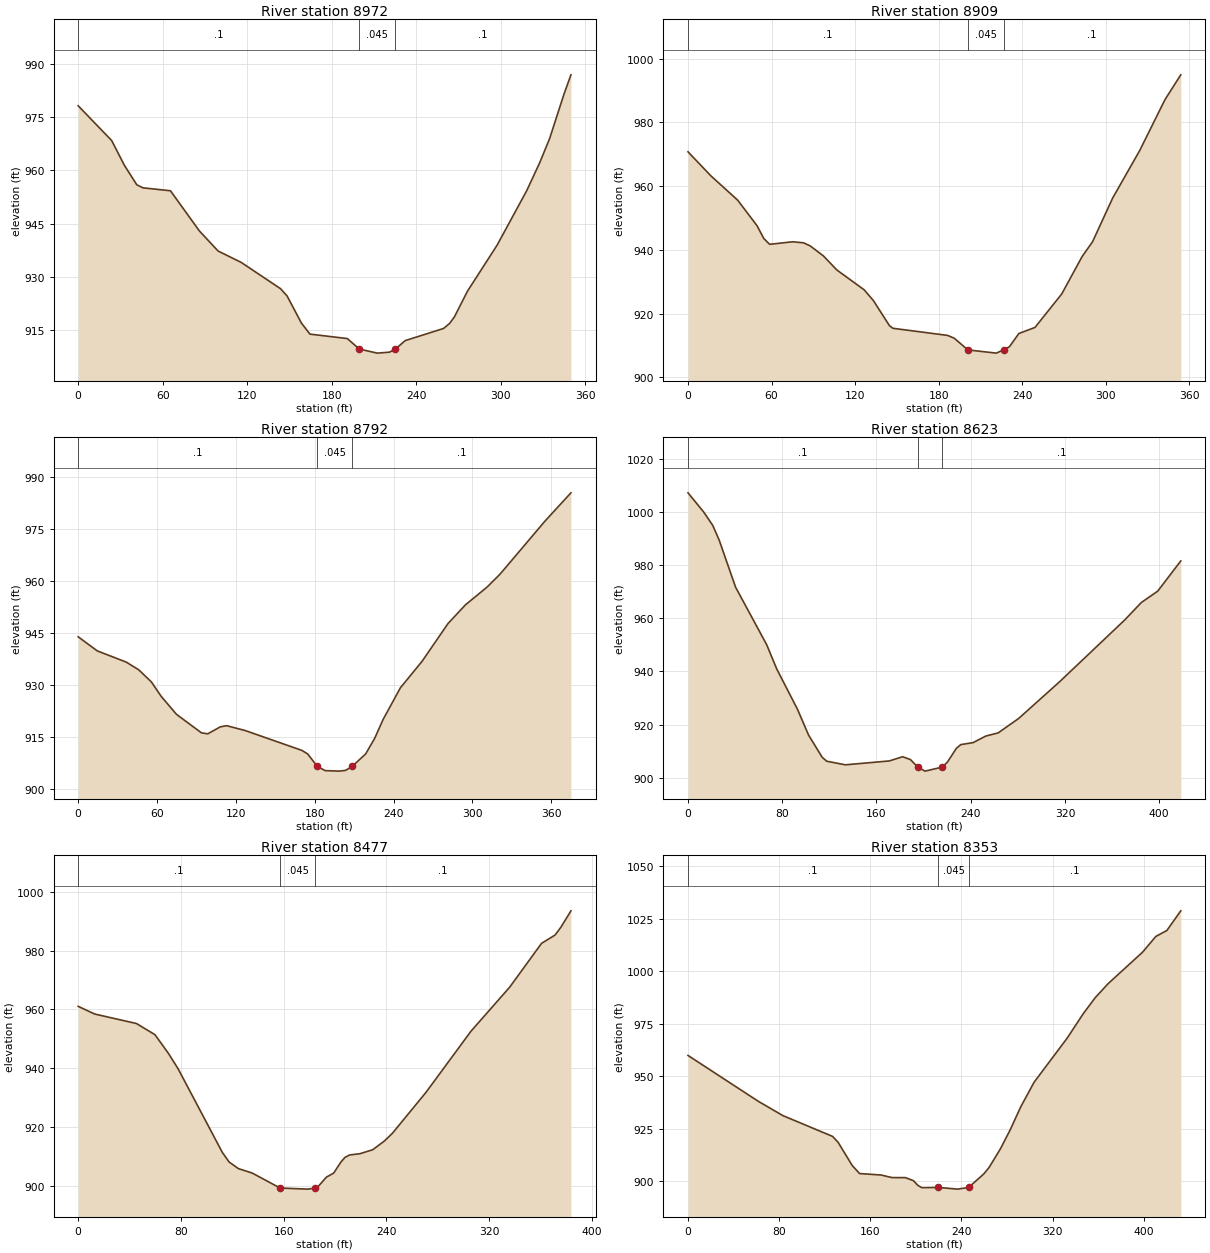
Type RM Length L Ch R = 1 ,8972    ,61,62.7,63.9
XS GIS Cut Line= 3
1657333.32318918466505.4394067761657231.98969216466616.530944257
1657104.38454775466769.657117543
#Sta/Elev= 30
       0   978.3    23.8  968.45    32.7  961.53    41.6  955.96      46   955.1
    65.5  954.27      86  942.93    99.3  937.24   115.7  934.02   143.7  926.57
   148.3  924.51   158.4   916.9   164.5  913.75     191   912.5   199.5  909.53
   212.3  908.38   220.9  908.65   225.1   909.5   225.1  909.51   232.1  911.92
   259.3  915.35   263.6  916.77     267  918.62   276.3   925.9   297.3  938.89
   318.3  954.28   327.6  962.25   334.6  969.05   344.7   981.5   349.7  987.04
#Mann= 3 ,-1,0
       0      .1       0   199.5    .045       0   225.1      .1       0
Bank Sta=199.5,225.1
XS Rating Curve= 0 ,0
Exp/Cntr(USF)=0,0
Exp/Cntr=0.3,0.1

Type RM Length L Ch R = 1 ,8909    ,117.1,117.1,117.2
XS GIS Cut Line= 3
1657298.91492884 466479.033219011657117.69013846466650.943307815
1657069.22755908466743.081309921
#Sta/Elev= 30
       0  970.77    16.3  963.28    35.7  955.58    49.6  947.56    54.4  943.57
    58.6  941.73    75.2  942.53      83   942.2    87.8  941.22    97.3  938.07
   106.9  933.67   126.5  927.45   133.2  924.03   144.6  916.24   147.1  915.37
   186.5  913.13   191.2  912.25  200.99908.5848   221.4  907.57  226.59908.5857
   230.8  909.56   237.6  913.72   249.2  915.64   268.4  926.14   283.1  937.93
   290.5   942.5     305  956.27   324.5  971.25   342.5  987.11   353.9  994.94
#Mann= 3 ,-1,0
       0      .1       0  200.99    .045       0  226.59      .1       0
Bank Sta=200.99,226.59
XS Rating Curve= 0 ,0
Exp/Cntr(USF)=0,0
Exp/Cntr=0.3,0.1

Type RM Length L Ch R = 1 ,8792    ,185.1,169,154
XS GIS Cut Line= 3
1657202.38965224466409.2686637671657041.75729399466561.644218556
1657030.49801655466714.770391842
#Sta/Elev= 30
       0  943.99    14.5  939.93    36.6  936.69    46.1  934.47    55.7  930.98
    63.2  926.81    74.8  921.64    93.8  916.31    98.6  916.03   108.1  918.03
   112.9  918.38   127.2  916.96   170.1  911.27   174.6  910.24  181.99906.6214
   187.9  905.43   198.7  905.28   203.5   905.5  208.41906.6208   218.7  910.23
   225.5  914.66     232  920.17   245.2  929.32   261.7  936.95   281.4  947.82
   294.7  953.21     311  958.28   320.9  962.01   355.1   977.3   374.9  985.47
#Mann= 3 ,-1,0
       0      .1       0  181.99    .045       0  208.41      .1       0
Bank Sta=181.99,208.41
XS Rating Curve= 0 ,0
Exp/Cntr(USF)=0,0
Exp/Cntr=0.3,0.1

Type RM Length L Ch R = 1 ,8623    ,154.8,145.8,139.9
XS GIS Cut Line= 4
1656817.70564136466347.8747039771656871.34335786466432.160893596
1656940.42379697466551.1355596051656999.47918111466722.072528952
#Sta/Elev= 30
       0 1007.11    13.2  999.96      21  994.86    26.4  989.41    40.4  971.63
    66.8  950.01    75.4  940.84    92.9  925.78   102.4  916.02   113.9  907.72
   117.7  906.24   133.6  904.88   170.9  906.34   182.2  907.92   188.8  906.85
  195.12903.9948   201.2  902.51  215.54903.9946   220.1  905.82   227.8  911.08
   231.6  912.48     242  913.22   252.9  915.71   263.3  916.88   280.7  922.31
   315.4  936.09     371  959.45   384.8  965.88   398.7  970.15   418.3  981.51
#Mann= 3 ,-1,0
       0      .1       0  195.12    .045       0  215.54      .1       0
Bank Sta=195.12,215.54
XS Rating Curve= 0 ,0
Exp/Cntr(USF)=0,0
Exp/Cntr=0.3,0.1

Type RM Length L Ch R = 1 ,8477    ,123.2,123.7,123.6
XS GIS Cut Line= 3
1656667.19866424466553.3874150951656882.62617274466651.718438136
1656979.45595879466762.059357121
#Sta/Elev= 30
       0  961.04    12.9  958.42    45.4   955.2    59.8   951.4    70.2  945.09
    77.8  939.82   112.2  911.42   117.5  908.14   124.7   905.9   135.5  904.38
   157.2  899.29   178.8  898.92  184.68899.2933   186.5  899.64   193.2  902.99
   198.9  904.37   204.5   908.1   207.7  909.71   211.3  910.53   219.3  910.95
   229.3  912.31   238.4  915.28   244.6  917.89   270.8  931.83   305.8   952.6
   335.9  967.54   360.7  982.44   371.2  985.26   375.7  987.87   383.6   993.5
#Mann= 3 ,-1,0
       0      .1       0   157.2    .045       0  184.68      .1       0
Bank Sta=157.2,184.68
XS Rating Curve= 0 ,0
Exp/Cntr(USF)=0,0
Exp/Cntr=0.3,0.1

Type RM Length L Ch R = 1 ,8353    ,252.5,270.9,283.3
XS GIS Cut Line= 5
1656617.75596001466577.9736235971656674.54488843466676.874344432
1656740.31739468466720.8565399291656800.49345635466749.527603879
1656916.79833293466877.106162153
#Sta/Elev= 30
       0  959.92    61.5  938.17    83.3  931.29   126.9  921.41   131.7  918.63
   144.2  907.51   150.6  903.74   169.5  903.04     179  901.82   190.8   901.8
   197.9  900.35   201.5  898.23   205.1  897.04   219.7  897.14   236.7  896.33
  246.34897.1376   259.6  903.57   264.3  906.68   274.2  915.49   282.9  924.67
   292.1  935.53   303.8  947.21   332.6  968.01   347.2  980.01   357.3  987.33
   368.8  994.11     399 1009.06   410.6 1016.53   420.3 1019.36   432.5 1028.71
#Mann= 3 ,-1,0
       0      .1       0   219.7    .045       0  246.34      .1       0
Bank Sta=219.7,246.34
XS Rating Curve= 0 ,0
Exp/Cntr(USF)=0,0
Exp/Cntr=0.3,0.1

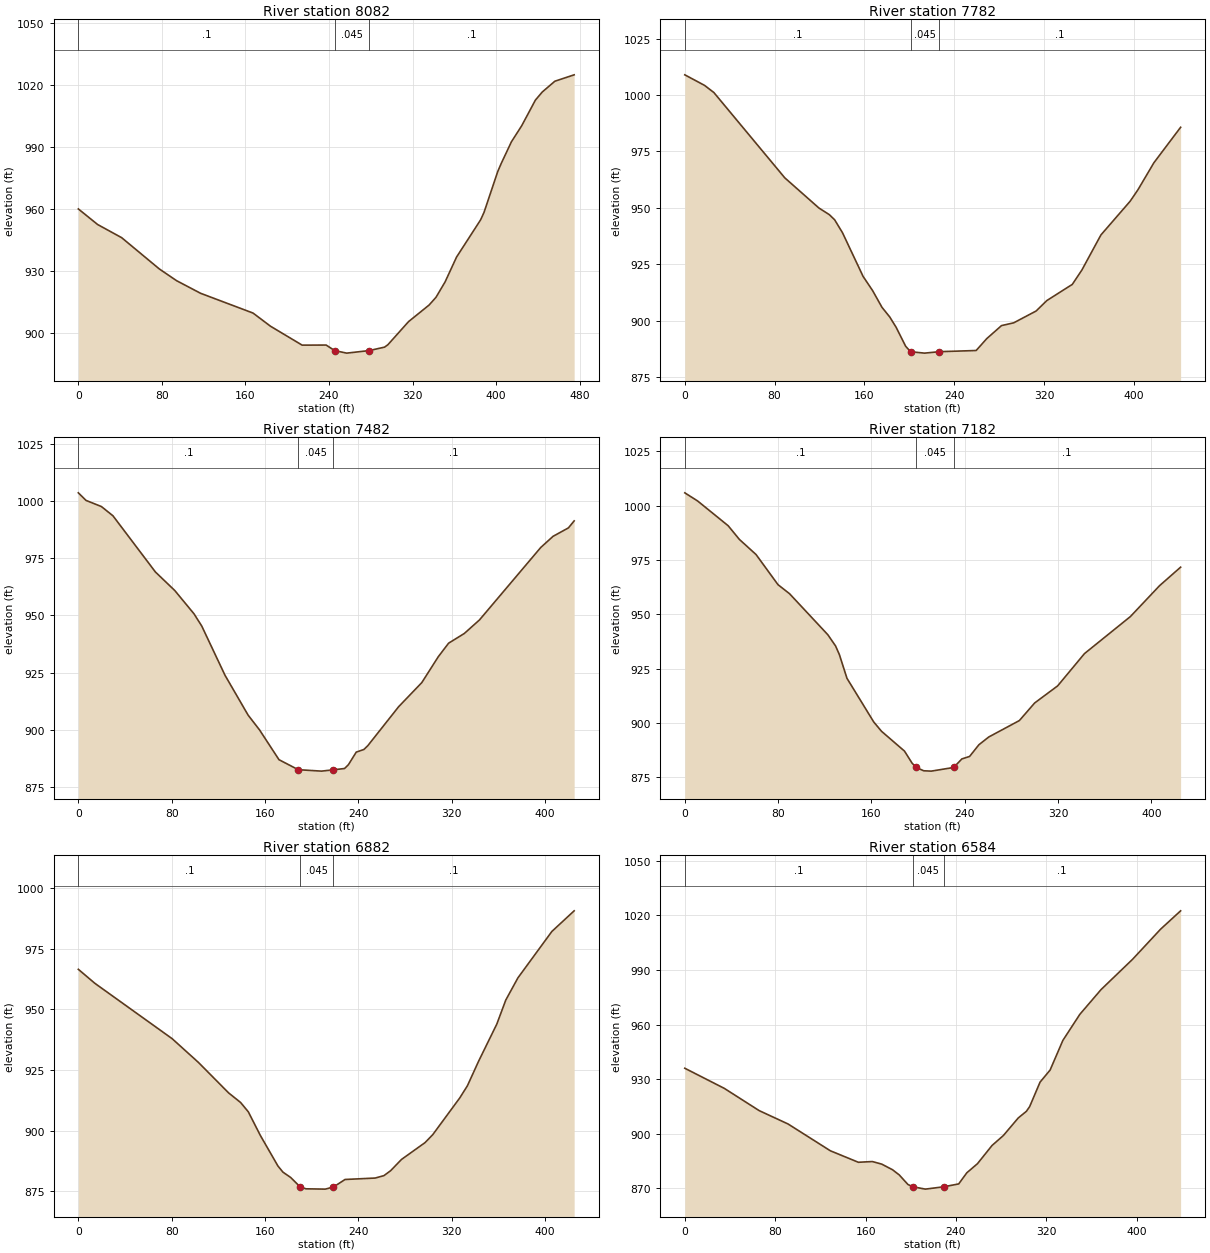
Type RM Length L Ch R = 1 ,8082    ,285.7,300.8,311.1
XS GIS Cut Line= 6
1656562.59750384466589.8833910081656554.37803209466717.931035176
1656535.98961742466799.9321835041656541.24616858466899.794188499
1656545.18776175466974.6903641671656549.78650583467062.069454506
#Sta/Elev= 30
       0  960.04    18.5  952.49    41.5  946.13    77.6  930.99    94.1  925.32
   117.1  919.22   167.3  909.66   184.1  903.27   214.3  894.15   237.3  894.18
  245.53891.4966     257  890.28  278.36 891.496   293.2  893.17   296.5  894.38
   316.2  905.51   335.9  913.55   342.5  917.29   351.2  924.72   362.2  936.76
   385.2  954.74   388.5  958.38   401.6   978.1   404.9  981.97   414.7  992.49
   424.6  1000.3   437.7 1012.69   444.3 1016.62   456.3 1021.81   474.8 1024.91
#Mann= 3 ,-1,0
       0      .1       0  245.53    .045       0  278.36      .1       0
Bank Sta=245.53,278.36
XS Rating Curve= 0 ,0
Exp/Cntr(USF)=0,0
Exp/Cntr=0.3,0.1

Type RM Length L Ch R = 1 ,7782    ,304.3,299.2,290.7
XS GIS Cut Line= 6
1656478.37621559466496.0102191721656424.65617867  466565.0783225
  1656378.610339466624.2793195841656315.99760334466702.266696423
1656259.27494776466755.3591099231656194.64876467466833.732312754
#Sta/Elev= 30
       0 1009.01    17.6 1004.33    25.9 1001.16    89.1  963.31   119.5  949.93
   128.8  946.97   133.5  944.71   140.5  938.98   158.9  919.56   167.3  913.33
   175.7  905.87   182.6   901.6   188.3  897.02   196.8  888.59   201.2  886.17
   213.6  885.55   226.9  886.19   259.6  886.71   269.1     892   282.2  897.76
   293.1     899     313  904.22   322.6  908.87   345.3  916.05   353.8   922.4
   370.8  937.99   396.8  952.92   403.8  958.04     418  970.01   441.8  985.74
#Mann= 3 ,-1,0
       0      .1       0   201.2    .045       0   226.9      .1       0
Bank Sta=201.2,226.9
XS Rating Curve= 0 ,0
Exp/Cntr(USF)=0,0
Exp/Cntr=0.3,0.1

Type RM Length L Ch R = 1 ,7482    ,302.3,300,299.7
XS GIS Cut Line= 6
1656096.62501059466395.1577305941656085.27299917466481.918055758
1656075.54270367466556.2843768451656062.56897634466655.439362258
1656052.83868083466729.8053552511656041.48634134466816.565680429
#Sta/Elev= 30
       0 1003.62     6.6  1000.3    19.8  997.61    29.7  993.56    66.1  968.97
    82.7  960.86    99.2  950.65   105.8  945.32   125.7  923.82   145.5  906.38
   155.4  899.83     172  886.85   188.5  882.48   208.4  881.85   218.3   882.4
   228.2     883   231.5  884.65   238.2  890.16   244.8  891.33   248.1  892.97
   274.6  910.06   294.4  920.58   308.6  931.95   317.4  937.84   330.8  942.06
   343.8  947.98   396.4  979.72   406.9  984.58   420.1  988.28     425  991.34
#Mann= 3 ,-1,0
       0      .1       0   188.5    .045       0   218.3      .1       0
Bank Sta=188.5,218.3
XS Rating Curve= 0 ,0
Exp/Cntr(USF)=0,0
Exp/Cntr=0.3,0.1

Type RM Length L Ch R = 1 ,7182    ,299,300,300.6
XS GIS Cut Line= 6
1655778.31003043466377.5593405961655774.85892184466464.991252333
1655771.90059443 466539.93270351 1655767.9563766466639.854747757
1655764.99804917466714.7965269981655761.54694059 466802.22843875
#Sta/Elev= 30
       0 1005.87      11 1002.12    37.2  990.72    46.8  984.43    61.1  977.47
    79.9  963.61    89.8  959.45   122.6  940.59   129.2  935.46   132.5  931.45
     139  920.55     162  900.42   168.6  896.18   188.3  887.06   194.8  881.53
  198.37879.5298   204.8     878   211.3  877.84  230.46879.5289   237.5  883.45
   244.1  884.59   252.1  889.97   260.5  893.53   286.8  901.11   299.9   909.2
   319.6  917.06   342.6  931.91     382  948.97   406.9  963.13     425  971.67
#Mann= 3 ,-1,0
       0      .1       0  198.37    .045       0  230.46      .1       0
Bank Sta=198.37,230.46
XS Rating Curve= 0 ,0
Exp/Cntr(USF)=0,0
Exp/Cntr=0.3,0.1

Type RM Length L Ch R = 1 ,6882    ,286.7,298.1,299.6
XS GIS Cut Line= 6
1655489.14197358466364.7706522491655481.38477126466451.926317841
1655474.73550634466526.6308928431655465.87003851466626.236992836
1655459.22077359466700.9418959171655451.46357125 466788.09723343
#Sta/Elev= 30
       0  966.48    14.1  960.74    80.4  937.92   102.9  928.16   128.8   915.6
   139.1  911.64   145.7  907.81     156  898.09   171.1  885.49   175.4  882.96
     182  880.77  190.28876.8354   195.1   876.1   211.6  875.97  218.69876.8355
   228.6  879.94   254.4  880.53   261.9  881.52   267.6  883.52     277  888.19
   297.2  895.13   303.8   898.4   326.9  913.49   333.5  918.52   343.1  928.64
   358.7  943.92   366.4  953.83   376.8  962.96   405.9  982.07     425  990.56
#Mann= 3 ,-1,0
       0      .1       0  190.28    .045       0  218.69      .1       0
Bank Sta=190.28,218.69
XS Rating Curve= 0 ,0
Exp/Cntr(USF)=0,0
Exp/Cntr=0.3,0.1

Type RM Length L Ch R = 1 ,6584    ,247.8,265.4,268.9
XS GIS Cut Line= 6
1655316.79389308466344.5223331751655252.79992659466421.494620174
1655206.53623959466481.9219927491655154.37853551466567.322740585
1655117.68471126466632.7336990091655074.87574175466709.046210423
#Sta/Elev= 30
       0  936.02      35  924.95    65.8  912.75    91.4   905.4   128.8  890.69
   153.6  884.37     166  884.77   174.3  883.35   183.8  880.28   189.8  877.42
   197.5  872.15  201.97870.9088   212.9  869.62  229.22870.9075   242.4  872.48
   249.6   878.6     259  883.59   271.9  893.59   281.9  899.04   295.1  908.71
   302.3  912.36   305.2  914.95   314.4  928.38   323.3  935.03   334.6  951.32
   349.6  965.62   368.4  979.23   396.3  995.87   421.1 1012.41   438.8 1022.48
#Mann= 3 ,-1,0
       0      .1       0  201.97    .045       0  229.22      .1       0
Bank Sta=201.97,229.22
XS Rating Curve= 0 ,0
Exp/Cntr(USF)=0,0
Exp/Cntr=0.3,0.1