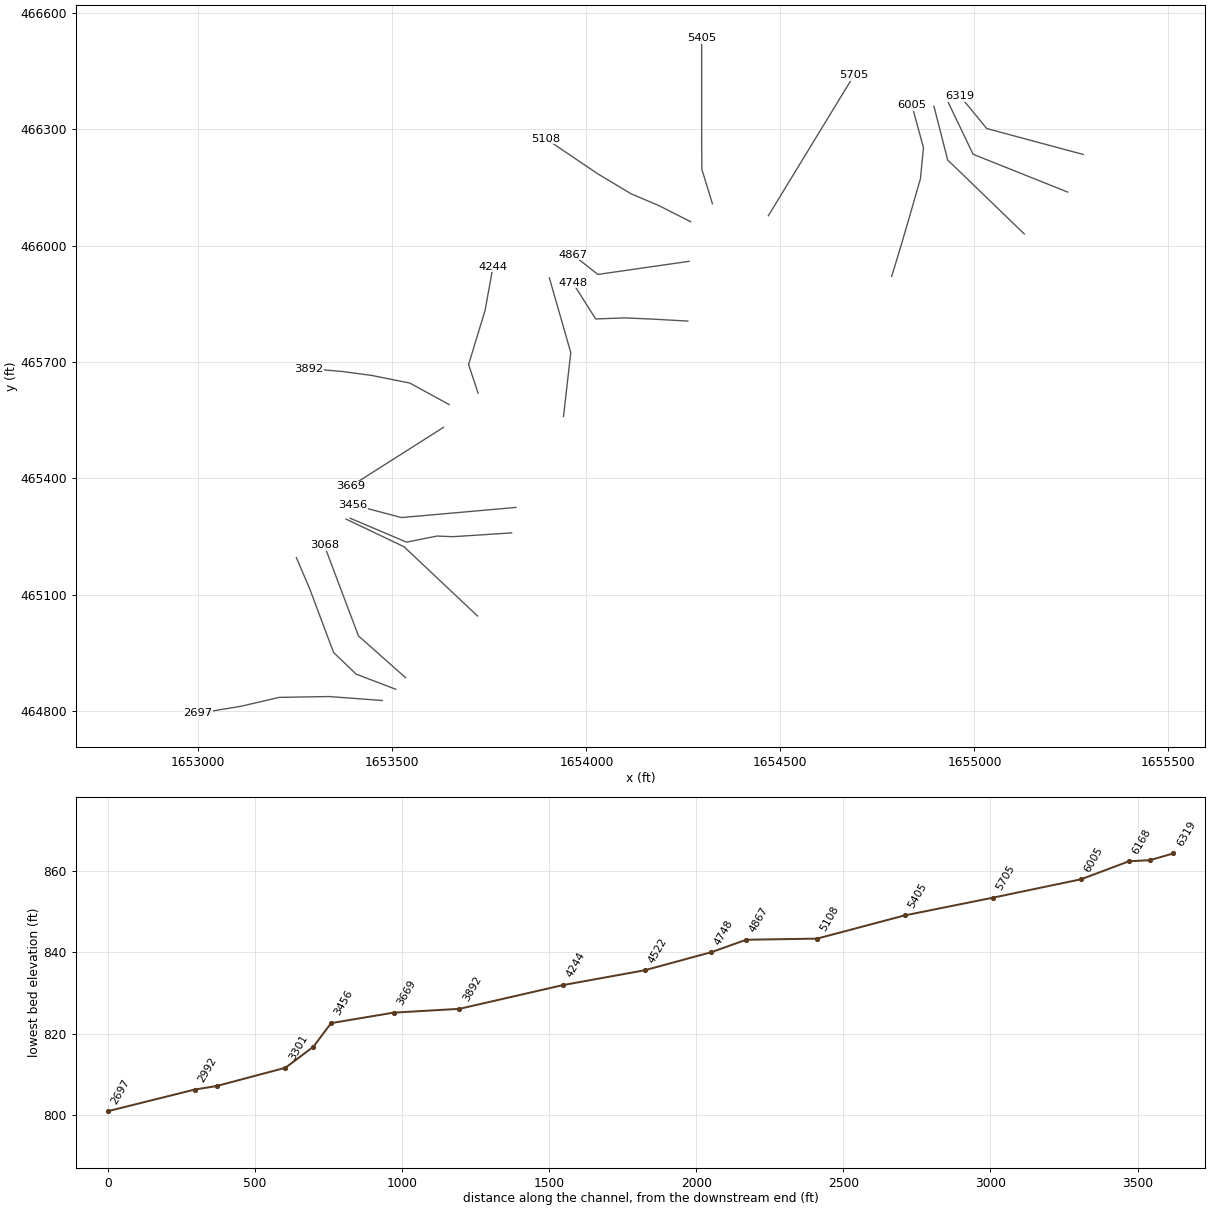
HEC-RAS study BigRnI.prj: BigRnI

--- BigRnI.g01 (geometry) --- (continued)

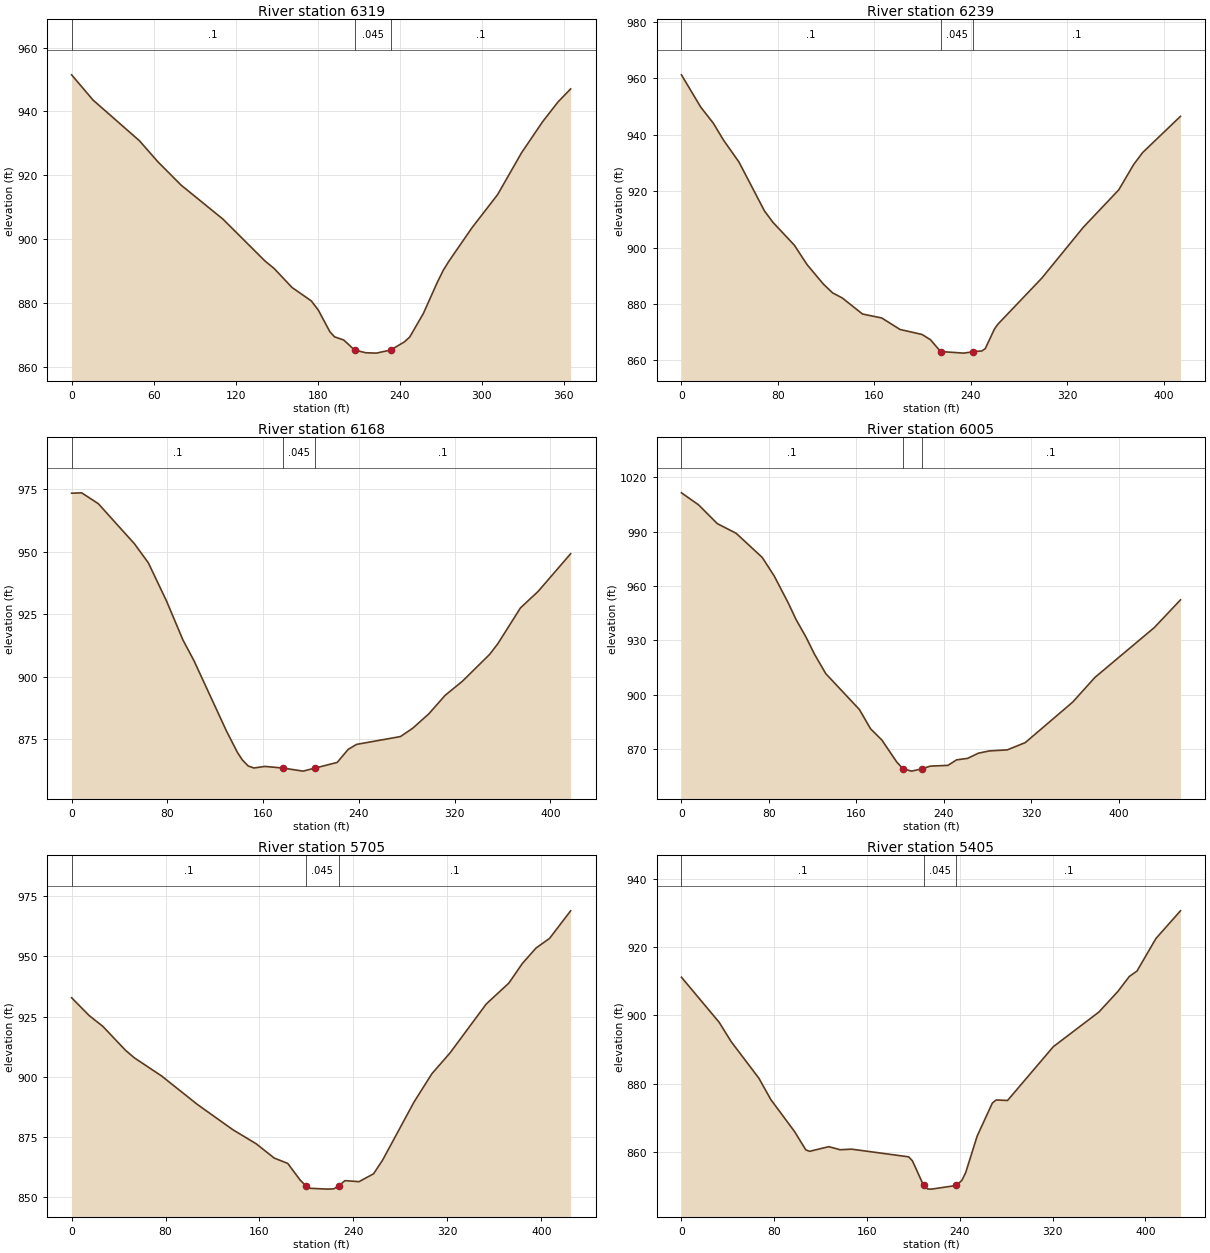
Type RM Length L Ch R = 1 ,6319    ,81.3,80.2,78.3
XS GIS Cut Line= 3
1655280.05568272 466235.125172581655031.60096037466301.930218768
1654963.29467719 466385.24887188
#Sta/Elev= 30
       0  951.48    15.7  943.56    49.6  930.83    63.2  924.18    80.2  916.88
   110.7  906.26   141.4  893.16   148.2  890.77   161.2  884.85   175.3  880.64
   180.4   877.8   188.9  870.99   192.3  869.38   199.1  868.37  206.97865.2307
   215.2  864.39   222.9  864.27  233.29865.2299   243.3  867.76   247.3   869.3
   257.3  876.71   267.4  886.37   271.9  890.27   275.9  893.03   292.9  903.59
   311.6  913.95   329.1  927.05   344.6  936.84   355.8  942.99     365  947.07
#Mann= 3 ,-1,0
       0      .1       0  206.97    .045       0  233.29      .1       0
Bank Sta=206.97,233.29
XS Rating Curve= 0 ,0
Exp/Cntr(USF)=0,0
Exp/Cntr=0.3,0.1

Type RM Length L Ch R = 1 ,6239    ,76.1,70.9,65.7
XS GIS Cut Line= 5
1655240.32312933466138.1151780181655159.07329184466170.592147185
1655089.43104268466198.4296899431654996.57427301466235.546413599
1654931.11259826 466372.12999291
#Sta/Elev= 30
       0  961.23    15.9  949.85    26.5  944.04    34.9  938.09    47.7  930.33
    68.9  912.98      76  908.91    93.6   900.9   104.2  893.98   117.8  887.05
   125.4  883.96   133.4  882.17   150.2  876.47   166.2  875.06   181.3     871
   199.6  869.22   206.6  867.36     215  863.17   234.3  862.61   241.9  863.12
   249.1  863.37     252  864.17   259.7  871.16   262.5  872.85     299   889.2
   333.4  907.21   362.8  920.47   375.2  929.47   382.6  933.68     414  946.52
#Mann= 3 ,-1,0
       0      .1       0     215    .045       0   241.9      .1       0
Bank Sta=215,241.9
XS Rating Curve= 0 ,0
Exp/Cntr(USF)=0,0
Exp/Cntr=0.3,0.1

Type RM Length L Ch R = 1 ,6168    ,174.9,162.7,151.1
XS GIS Cut Line= 3
1655128.43074642466030.2063230361654931.01808184466220.863421147
1654895.73901251466358.977224502
#Sta/Elev= 30
       0  973.36     8.4  973.51    22.3  969.18    52.5  953.16    64.1  945.57
    79.4  930.21      93  914.76   102.2   906.5   129.5  878.28   138.6  869.78
   142.7   866.8   147.6  864.39   152.3  863.59   161.5  864.22   176.6863.5659
   193.4  862.34  203.52863.5659   221.9  865.81   231.1  871.02   238.1  873.02
   274.8  876.15     285  879.46   298.5  885.22   312.1   892.6   326.6  898.26
   349.3  908.96   356.1  913.19   375.1  927.55   389.9  934.16     417  949.18
#Mann= 3 ,-1,0
       0      .1       0   176.6    .045       0  203.52      .1       0
Bank Sta=176.6,203.52
XS Rating Curve= 0 ,0
Exp/Cntr(USF)=0,0
Exp/Cntr=0.3,0.1

Type RM Length L Ch R = 1 ,6005    ,302.8,300,297.3
XS GIS Cut Line= 6
1654786.73294534465920.7859759181654812.17974484466004.513498753
1654833.19545084466076.5094177571654860.89093351466172.597808257
1654868.61795217466252.7272411731654838.64360267466362.397625506
#Sta/Elev= 30
       0 1011.36    15.7 1004.73    32.8  994.38      50  989.07      74  975.71
      85  965.41    97.9  950.46   104.8  941.61   114.1  931.68   121.9  922.23
   132.1  911.66   162.9  891.86   173.1  881.24   183.4  875.08     197  862.98
  202.77859.1909   210.7  857.92  219.92859.1879   227.7  860.67   243.9   861.1
   251.8  864.13   261.9  864.96   271.8  867.82   281.7  869.05   298.2  869.64
   314.6  873.62     358  895.94   378.4  909.58   432.8  937.09   456.7  952.34
#Mann= 3 ,-1,0
       0      .1       0  202.77    .045       0  219.92      .1       0
Bank Sta=202.77,219.92
XS Rating Curve= 0 ,0
Exp/Cntr(USF)=0,0
Exp/Cntr=0.3,0.1

Type RM Length L Ch R = 1 ,5705    ,293.5,300,308.6
XS GIS Cut Line= 6
1654468.91041826466077.1396658421654514.47003843466151.842928499
1654553.52114142466215.8739684221654605.58927876466301.249125749
1654644.64070985466365.280493751   1654690.20033466439.983756423
#Sta/Elev= 30
       0  932.79      15  925.37    26.6  920.92    45.8  911.03    53.5  907.83
    76.5  900.38   107.3  888.45   137.3  878.05   157.2   872.2   172.6  866.27
   184.1  864.05   194.6  857.17  199.64854.6998   203.3  853.73   218.2  853.39
   223.3  853.52  227.42 854.698   232.8  856.91   244.8  856.49   257.1  859.73
   264.8  865.38   291.7  889.58   306.8  901.24   322.5  910.02   353.2  930.22
   372.4  938.86   383.9     947   395.5  953.39   407.1  957.43     425  968.84
#Mann= 3 ,-1,0
       0      .1       0  199.64    .045       0  227.42      .1       0
Bank Sta=199.64,227.42
XS Rating Curve= 0 ,0
Exp/Cntr(USF)=0,0
Exp/Cntr=0.3,0.1

Type RM Length L Ch R = 1 ,5405    ,286.6,297.3,313.1
XS GIS Cut Line= 6
1654324.78636268466108.1369791781654297.52263768466196.812326759
1654297.07841285466271.8125048431654297.07841285466371.812632918
1654297.07841285466446.8124829231654297.07841285466534.312307924
#Sta/Elev= 30
       0  911.17    32.5  897.96    42.8  892.32    66.8  881.54    77.1  875.28
    97.5  865.93   107.3  860.51   110.6  860.12     127  861.48   136.9  860.58
   146.7  860.75   195.9   858.5   199.2  857.31   208.8850.1062   212.3  849.06
   215.6  849.03  237.08850.1097   241.8  851.59   245.1  853.88     255  864.59
   268.1  874.28   271.4  875.18   281.2  875.03   320.6  890.78     360  900.97
   376.4  907.03   386.2   911.4   392.8  912.97   409.2  922.55   430.3  930.64
#Mann= 3 ,-1,0
       0      .1       0   208.8    .045       0  237.08      .1       0
Bank Sta=208.8,237.08
XS Rating Curve= 0 ,0
Exp/Cntr(USF)=0,0
Exp/Cntr=0.3,0.1

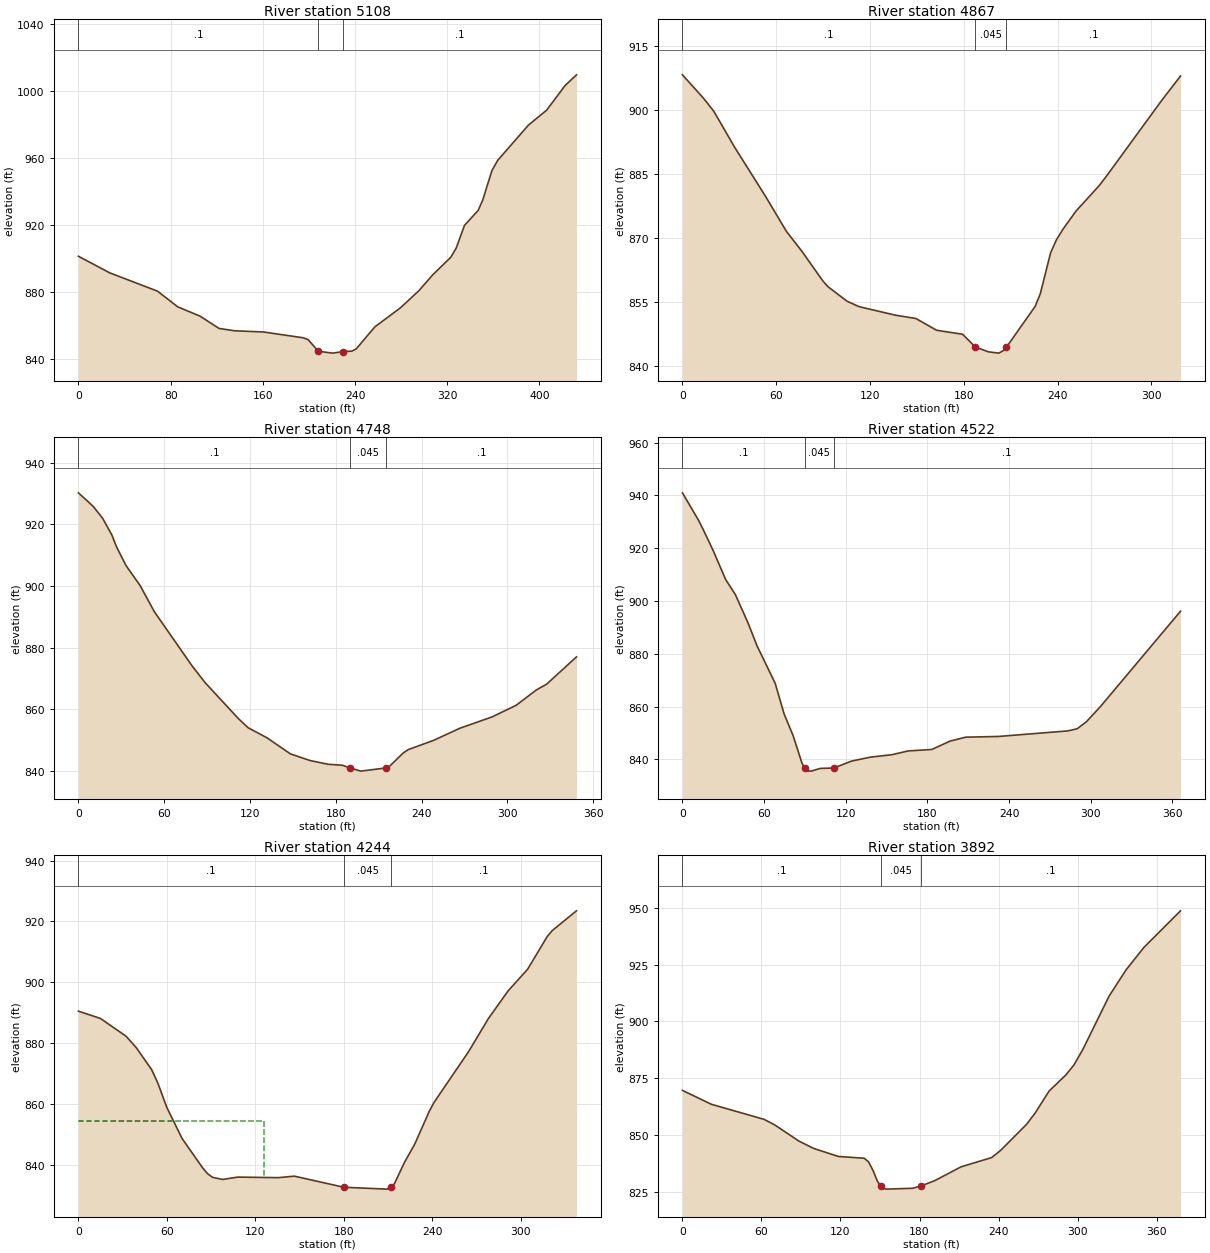
Type RM Length L Ch R = 1 ,5108    ,231,240.9,245.9
XS GIS Cut Line= 6
1654268.97381026466061.5796575841654185.89753284 466103.69833976
1654115.58599368466133.4728865031654029.67343584466184.938662842
1653967.52920318466226.9280801711653895.02737968466275.915186927
#Sta/Elev= 30
       0  901.26    27.3   891.3    68.6   880.4    86.2     871   105.5  865.47
     122   858.1   135.5   856.7   160.5  855.99     195  852.52   199.2  851.45
  208.22844.4149   220.7  843.34   229.5  844.28   237.1  844.51   240.9   845.8
   257.2  859.06   279.5   870.5   295.4   880.7   307.2  890.02   323.1  900.71
   327.7   906.1   334.9  919.72   346.8  928.67   350.8  934.93   358.7  952.44
   363.7  958.57   390.4  979.68   406.2  988.63   422.3 1003.43   432.1 1009.76
#Mann= 3 ,-1,0
       0      .1       0  208.22    .045       0   229.5      .1       0
Bank Sta=208.22,229.5
XS Rating Curve= 0 ,0
Exp/Cntr(USF)=0,0
Exp/Cntr=0.3,0.1

Type RM Length L Ch R = 1 ,4867    ,120.7,118.9,119.4
XS GIS Cut Line= 3
1654264.46885695465959.6481843661654029.52526755465925.870352023
1653965.72269535465976.161791289
#Sta/Elev= 30
       0  908.28    13.5  902.78    20.1  899.71    33.3  891.35    53.2  879.77
    66.5  871.59    76.4  866.93    89.7  860.03      93  858.65   105.3  855.22
   112.9  853.96   136.1  851.96   149.3  851.18   162.6  848.42   179.2  847.48
  187.45  844.47   195.8  843.36   202.4  843.06   205.7  843.75  207.28844.4705
   225.6     854   228.9  856.97   235.5  866.57   239.2   869.6   243.4   872.1
   251.8  876.38   266.5  882.28   271.2  884.52   306.4   902.2   318.6     908
#Mann= 3 ,-1,0
       0      .1       0  187.45    .045       0  207.28      .1       0
Bank Sta=187.45,207.28
XS Rating Curve= 0 ,0
Exp/Cntr(USF)=0,0
Exp/Cntr=0.3,0.1

Type RM Length L Ch R = 1 ,4748    ,237,226.2,197.3
XS GIS Cut Line= 5
1654261.44163182465805.6802869261654173.65506199465810.584476602
1654098.43998931465813.9023833541654023.95367228465811.144551012
1653964.71094649465904.573110361
#Sta/Elev= 30
       0  930.18    10.3   925.8    16.9  921.96    23.4  916.49    26.7  912.63
    33.3   906.6    43.2   900.1      53  891.73    79.3  874.23    88.7  868.63
   111.6  857.16   118.7  854.06   131.9   850.8   148.3  845.59     162  843.44
   174.5  842.23   184.4  841.92  190.16841.0453   197.5     840  215.33841.0457
   217.2  841.38   227.1  845.84   230.7  846.97   248.5  849.98   266.8  853.89
   289.4  857.58   306.1   861.3   320.3  866.29   327.5  868.17   348.4  877.02
#Mann= 3 ,-1,0
       0      .1       0  190.16    .045       0  215.33      .1       0
Bank Sta=190.16,215.33
XS Rating Curve= 0 ,0
Exp/Cntr(USF)=0,0
Exp/Cntr=0.3,0.1

Type RM Length L Ch R = 1 ,4522    ,272.5,277.8,272.6
XS GIS Cut Line= 3
1653941.07050005465559.7627396611653959.71774738465724.527227643
1653904.60028121465916.904551668
#Sta/Elev= 30
       0     941    11.9  930.51    15.2  927.13    22.7  918.97    31.7  908.18
    38.9  902.42    48.2  891.66    54.8  883.01    68.1  868.85    74.7  857.19
    81.3  848.98    87.9  838.44 90.0199836.5734    91.2  835.59    94.5  835.56
   101.2  836.59111.0896836.7344   124.2  839.36   138.1  840.86   153.9  841.79
   165.8  843.21   183.2  843.76   196.5  846.92   208.1  848.43     232  848.69
   283.2   850.8     290  851.61   296.8  854.29   307.1  860.04   365.9  896.14
#Mann= 3 ,-1,0
       0      .1       0 90.0199    .045       0111.0896      .1       0
Bank Sta=90.0199,111.0896
XS Rating Curve= 0 ,0
Exp/Cntr(USF)=0,0
Exp/Cntr=0.3,0.1

Type RM Length L Ch R = 1 ,4244    ,314.6,351.9,369.4
XS GIS Cut Line= 4
 1653720.9676527465619.6824303751653696.47579483465693.645798346
1653738.98918165465833.6249733561653759.25588106465945.405129689
#Sta/Elev= 30
       0  890.46    14.9  888.07    32.3  882.22    39.2  878.47    49.6  871.27
    53.9  866.76      60  858.73    70.3  848.58    84.1     839    87.5  837.03
      91  835.79    97.8   835.1   108.1  835.88   135.5  835.69   146.4  836.19
     180  832.54   209.1  831.92  212.17832.5022   214.4  833.77   221.2  840.78
     228  846.62     238  857.56   241.3  860.53   264.7   877.2     278  887.98
   291.4  897.11   304.7  904.27     318  915.04   321.4  916.99   337.8  923.46
#Mann= 3 ,-1,0
       0      .1       0     180    .045       0  212.17      .1       0
#XS Ineff= 2 , 0
          125.97  854.47
Permanent Ineff=
       F       F
Bank Sta=180,212.17
XS Rating Curve= 0 ,0
Exp/Cntr(USF)=0,0
Exp/Cntr=0.3,0.1

Type RM Length L Ch R = 1 ,3892    ,210.8,223.2,232.7
XS GIS Cut Line= 5
1653646.17942621465590.5732630391653544.92867042465645.955488846
1653446.87112376465665.567654341  1653372.474619465675.543028086
1653285.08601426465683.317946926
#Sta/Elev= 30
       0  869.59      22  863.47    62.1  856.81    69.9  854.45    88.3  847.31
    99.5  844.05   118.4  840.48     138  839.71   141.3  838.12   144.7  834.32
     148  829.61  150.43827.4975   151.3  826.73   154.7  826.09   174.8  826.46
  181.16 827.498   191.5  829.81   211.6  835.93   234.8  839.99   241.4  843.06
   261.3  854.64   267.9  859.68   278.4   869.3     291  876.33   297.2  880.74
   304.1  887.71     324  911.18   336.9  922.75   350.3  932.54   378.2  948.73
#Mann= 3 ,-1,0
       0      .1       0  150.43    .045       0  181.16      .1       0
Bank Sta=150.43,181.16
XS Rating Curve= 0 ,0
Exp/Cntr(USF)=0,0
Exp/Cntr=0.3,0.1

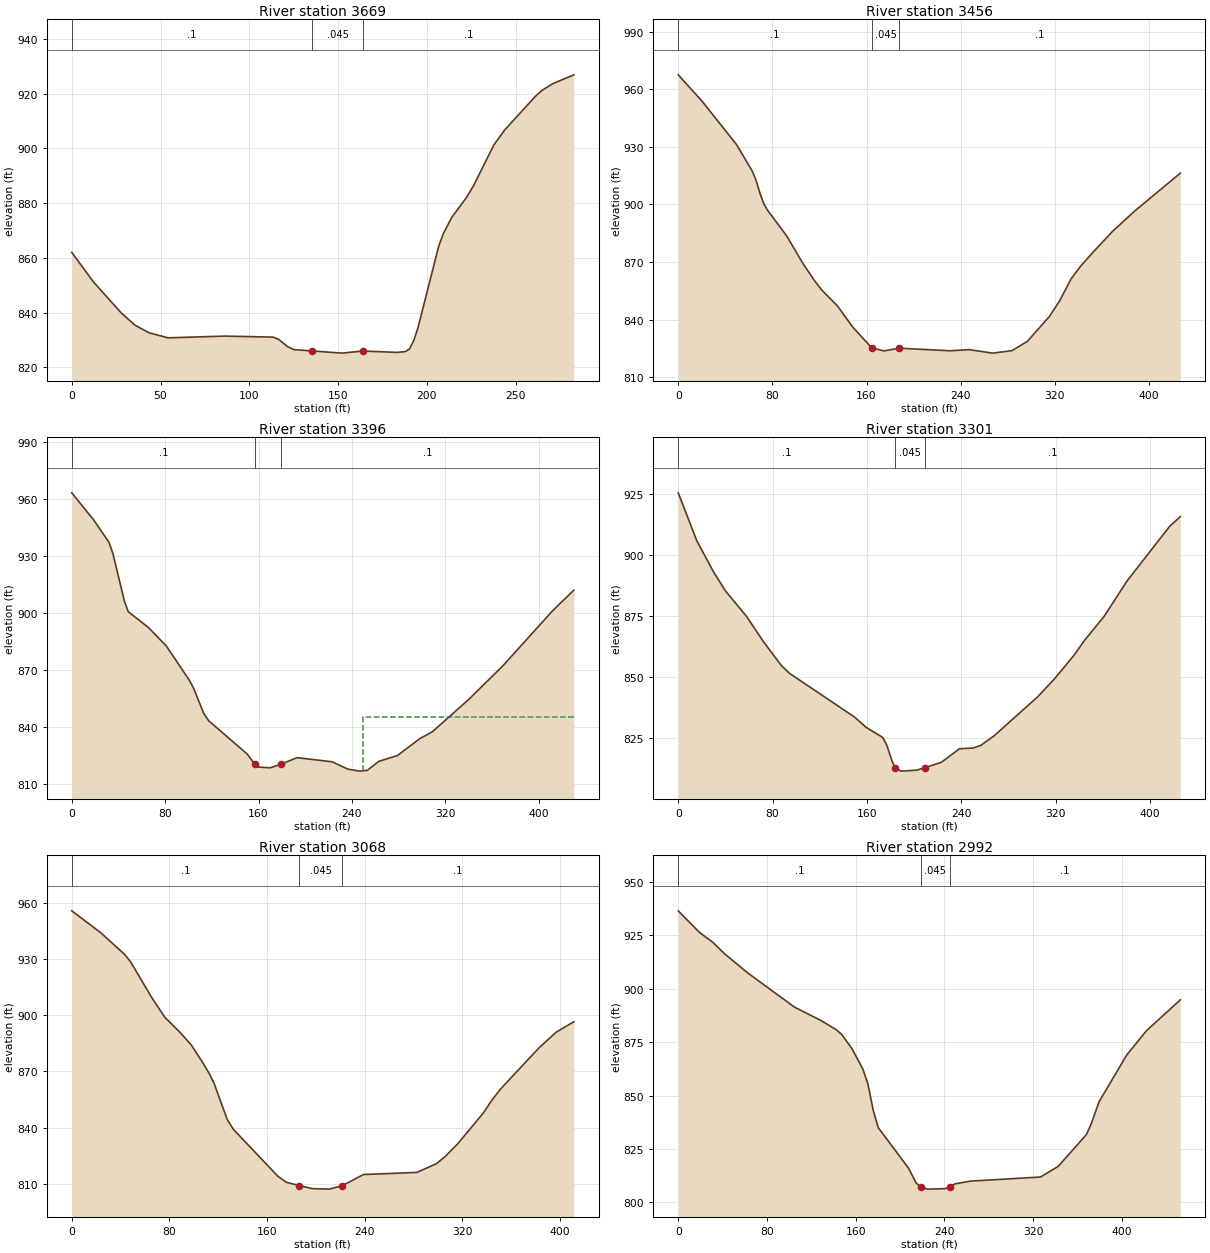
Type RM Length L Ch R = 1 ,3669    ,217,212.8,207.4
XS GIS Cut Line= 2
1653631.69746441465531.7956413621653393.00078252 465380.17070507
#Sta/Elev= 30
       0  862.01    12.4  851.04    27.9  839.84    35.7  835.33    43.5  832.63
    54.2  830.75    86.2  831.39   113.4  831.01   116.6  830.17   121.5  827.57
   125.1  826.44  135.42825.9665   152.2  825.16   164.1  825.93   183.1  825.43
   187.9  825.73   190.3  826.72   192.7  829.88     195  834.42   206.7   864.3
   209.3  868.87     214  874.75   222.3  882.05   226.2  886.27   237.8  901.35
   243.9  906.81   261.1  919.02     265  921.32   271.1  923.74   282.8  926.93
#Mann= 3 ,-1,0
       0      .1       0  135.42    .045       0   164.1      .1       0
Bank Sta=135.42,164.1
XS Rating Curve= 0 ,0
Exp/Cntr(USF)=0,0
Exp/Cntr=0.3,0.1

Type RM Length L Ch R = 1 ,3456    ,61.1,59.7,58.1
XS GIS Cut Line= 3
1653818.28816963465325.436804151 1653523.2921731465299.335321986
1653397.21708943465332.824016084
#Sta/Elev= 30
       0  967.47      20  953.92    49.6  931.12    62.8  917.47    66.1  912.61
    69.4  905.86    72.7   900.4    75.7  897.14    92.4  883.37   105.6  869.61
   115.5  860.56   122.1  855.33   135.2  847.22   148.4  836.05  164.43825.3252
   174.8  823.73   187.9  825.16   230.8   823.8   247.2  824.41     267  822.58
   283.5  823.86   296.6  828.67   315.4  841.68   323.8  849.54   333.8  861.23
   342.1  868.02   352.8  875.33   368.9   885.9   387.7  896.49   426.6  916.28
#Mann= 3 ,-1,0
       0      .1       0  164.43    .045       0   187.9      .1       0
Bank Sta=164.43,187.9
XS Rating Curve= 0 ,0
Exp/Cntr(USF)=0,0
Exp/Cntr=0.3,0.1

Type RM Length L Ch R = 1 ,3396    ,102.6,95.3,87.3
XS GIS Cut Line= 6
1653807.28943186465259.8274181661653656.52242151465250.023181908
1653615.48235521 465251.664784561653597.38317279465248.226759426
1653536.80803493465235.9147395371653391.52620025465297.474838981
#Sta/Elev= 30
       0  963.33    18.8  949.03    31.9  937.29    35.2  931.48    45.1  906.29
    48.4  900.73    65.9  892.31    81.2  882.55     101  864.42   104.3  860.56
   113.2  847.05   117.4  843.26   150.3  825.82   156.8  820.45   160.1  818.92
     170  818.57  179.46820.4481     193   823.9   223.1  821.71   236.5  817.88
   246.5   816.8   253.2  817.21   263.2  821.98   278.9  824.96   298.3  833.94
     309  837.52   340.1  854.53   369.5  872.32   412.3  901.43   430.2  912.07
#Mann= 3 ,-1,0
       0      .1       0   156.8    .045       0  179.46      .1       0
#XS Ineff= 2 , 0
                          249.46          845.25
Permanent Ineff=
       F       F
Bank Sta=156.8,179.46
XS Rating Curve= 0 ,0
Exp/Cntr(USF)=0,0
Exp/Cntr=0.3,0.1

Type RM Length L Ch R = 1 ,3301    ,240.7,232.7,226
XS GIS Cut Line= 3
1653719.29952973465045.7624323661653530.18690423465224.040480355
1653380.47274239 465295.45019571
#Sta/Elev= 30
       0  925.34    15.7  905.82      30  892.98    40.1  885.23    58.1  874.75
    72.3   864.5    87.4  854.79    94.2  851.64   149.6  833.69   159.2  829.56
   173.5  825.36   176.8  822.31   181.4  815.65  184.07813.0139   188.9  811.62
   202.4  812.03  209.07813.0125   223.2  815.25   238.5  820.76   250.1  821.06
   256.5  822.11   268.1  826.14   304.7  841.93     319  849.27   335.7  858.99
   344.4  864.95   361.3  874.93   380.7  889.37   417.1  911.83   425.8   915.6
#Mann= 3 ,-1,0
       0      .1       0  184.07    .045       0  209.07      .1       0
Bank Sta=184.07,209.07
XS Rating Curve= 0 ,0
Exp/Cntr(USF)=0,0
Exp/Cntr=0.3,0.1

Type RM Length L Ch R = 1 ,3068    ,76.5,76.2,78.7
XS GIS Cut Line= 3
1653533.97742394464886.7379973131653412.70694592464994.279741972
1653324.61424019465227.668209104
#Sta/Elev= 30
       0  955.79    23.6  944.18    43.3  932.53    48.2   928.6    65.4  909.64
    76.3   898.9    87.8  891.51      98  884.12   107.3  874.75   112.5  869.07
   116.6  863.75   127.3  844.51   132.3  839.21     169  813.98     176   810.8
   186.5  809.04   197.1  807.43   211.1  807.15   221.6  808.95   239.1  814.95
   282.8  816.07   298.8  820.71   305.5  824.24   316.3  831.34   337.3  847.78
   344.3  854.65   351.5  860.67   382.9  882.57   396.9   890.9   411.5  896.55
#Mann= 3 ,-1,0
       0      .1       0   186.5    .045       0   221.6      .1       0
Bank Sta=186.5,221.6
XS Rating Curve= 0 ,0
Exp/Cntr(USF)=0,0
Exp/Cntr=0.3,0.1

Type RM Length L Ch R = 1 ,2992    ,272.7,295.3,304.6
XS GIS Cut Line= 6
1653508.92972668464856.7720278351653406.67500992464895.889075592
1653348.53897133464951.5615364161653313.42618068465045.193895087
1653287.09158768465115.4188202621653252.67334943465195.961966261
#Sta/Elev= 30
       0  936.41    19.4  926.18    30.8  921.88    41.3  916.53    62.4  907.46
   104.6  891.44   128.3  885.21   142.5  880.81   147.3  878.63   156.7  871.88
   166.5  862.31     171  855.43   175.8  843.05   180.3  835.01   207.5  816.13
   214.5  809.12  218.72 807.191     225  806.25   240.6  806.47   244.7807.1912
   249.5  808.72   263.5     810   326.6  811.91   342.6  816.93     368  831.79
   372.3  836.79   379.4  847.15   404.4  869.05   422.2  880.39   452.6  894.78
#Mann= 3 ,-1,0
       0      .1       0  218.72    .045       0   244.7      .1       0
Bank Sta=218.72,244.7
XS Rating Curve= 0 ,0
Exp/Cntr(USF)=0,0
Exp/Cntr=0.3,0.1

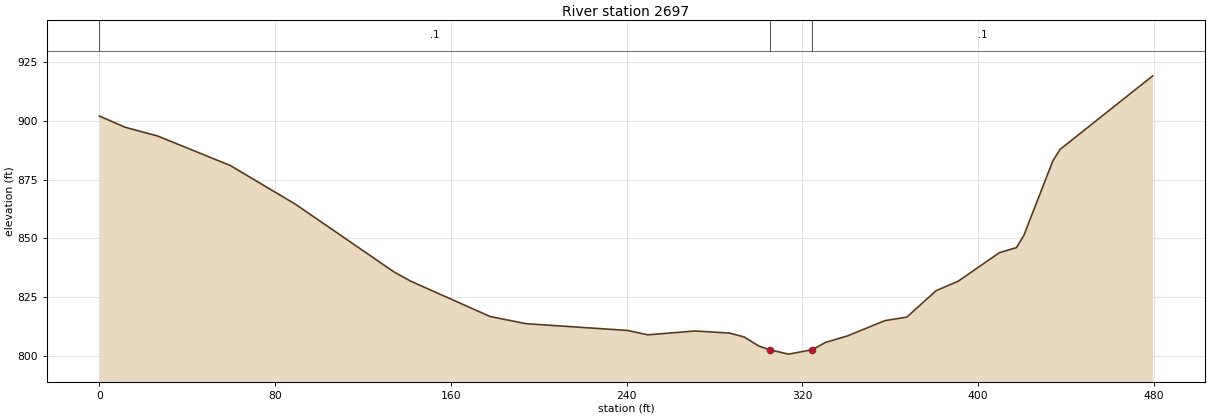
Type RM Length L Ch R = 1 ,2697    ,138.8,147.6,155.2
XS GIS Cut Line= 6
1653473.99246059464827.8754320891653336.80080584464838.095884085
1653208.79056318464835.974825338 1653110.0069681 464813.06706275
1653036.02548876464800.8525202571652999.04470864464794.712181265
#Sta/Elev= 30
       0  901.93    11.7  897.18    26.7  893.39    59.6  880.94    89.2  864.56
   134.1  835.82   141.8  831.86   177.9  816.88   194.3  813.84   240.3  810.99
   249.7  809.13   271.2  810.76   286.8  809.87   293.5  808.23   300.2  804.37
   305.1802.8137   313.7  800.94  324.57802.8144   330.5   805.9   340.6  808.69
   357.5  815.12   367.6  816.67   380.9  827.86   390.9  831.84   409.7  843.96
   417.5  846.14   420.8  851.24   434.1  883.04   437.4  887.83   479.5  918.97
#Mann= 3 ,-1,0
       0      .1       0   305.1    .045       0  324.57      .1       0
Bank Sta=305.1,324.57
XS Rating Curve= 0 ,0
Exp/Cntr(USF)=0,0
Exp/Cntr=0.3,0.1