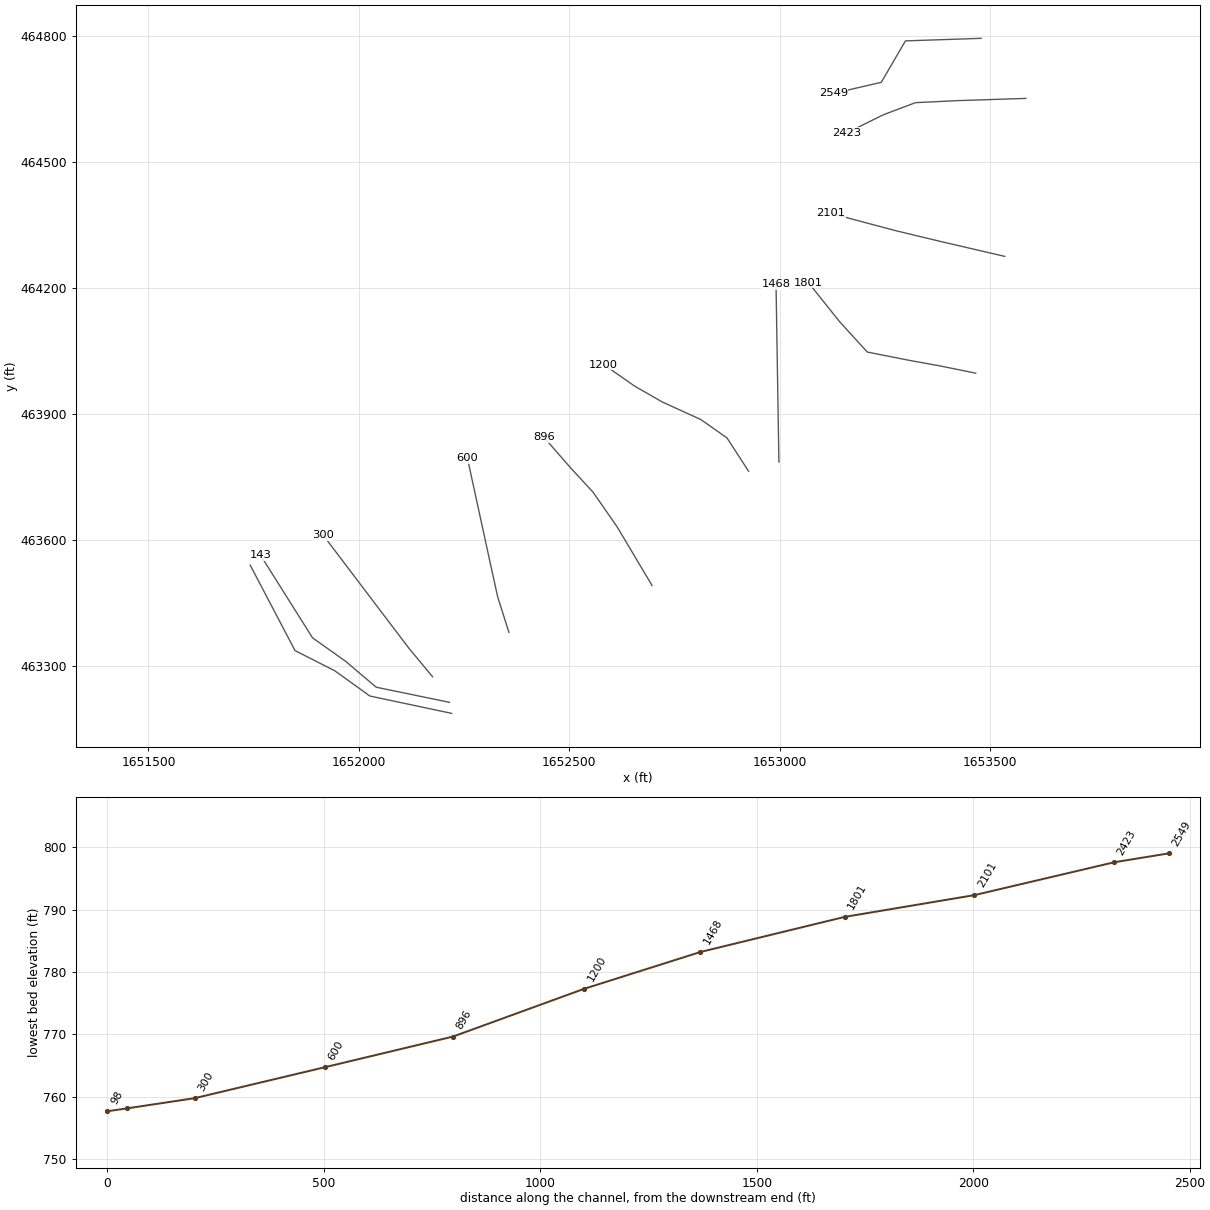
HEC-RAS study BigRnI.prj: BigRnI

--- BigRnI.g01 (geometry) --- (continued)

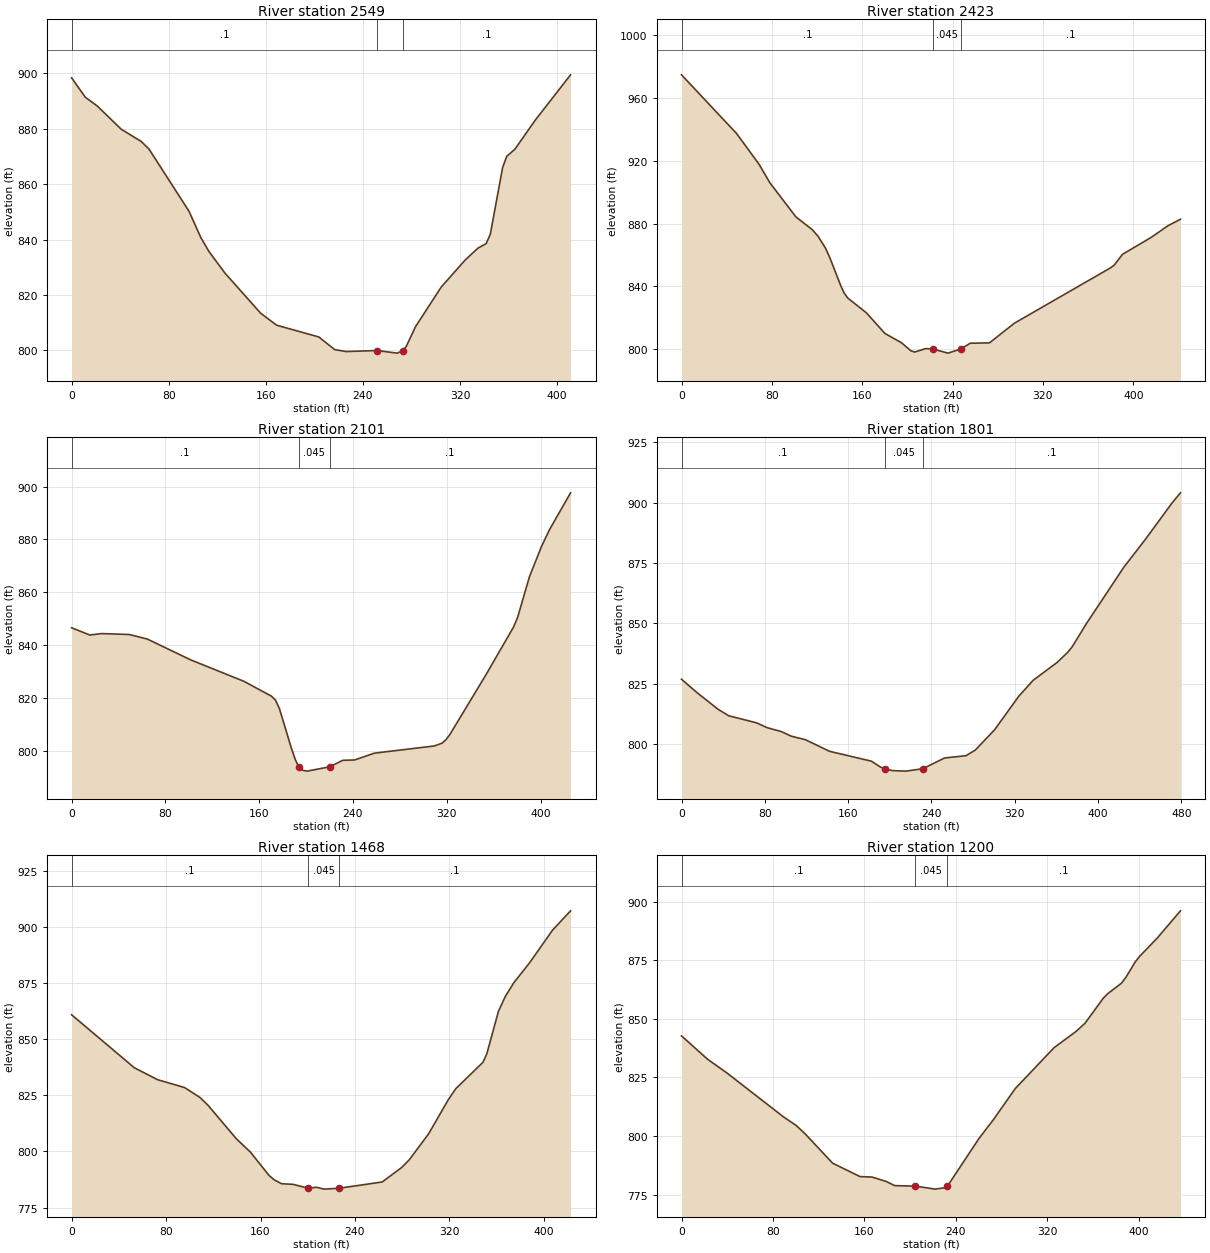
Type RM Length L Ch R = 1 ,2549    ,135.5,126,111.5
XS GIS Cut Line= 4
 1653478.3391693464794.5075657531653298.64110124464788.427555931
1653241.21878626464689.7962854911653127.04971294464663.449576264
#Sta/Elev= 30
       0  898.38    11.3  891.39    21.2   888.2    40.8  879.87    57.3  875.44
    63.8  872.66    96.7  850.26   106.5  840.73   113.1  835.76   126.2     828
   155.7  813.47   168.9  809.12   203.7  804.87   216.8   800.3   226.4  799.61
   251.7  799.98   268.2  799.04  272.76799.8757   275.8  801.52   283.4  808.62
   304.6  822.92   324.3  832.66   334.9  836.95   341.6  838.56     345  841.97
   355.1  865.98   358.5  870.06   365.2   872.6     382  883.11   411.1  899.47
#Mann= 3 ,-1,0
       0      .1       0   251.7    .045       0  272.76      .1       0
Bank Sta=251.7,272.76
XS Rating Curve= 0 ,0
Exp/Cntr(USF)=0,0
Exp/Cntr=0.3,0.1

Type RM Length L Ch R = 1 ,2423    ,326.7,322.6,319.6
XS GIS Cut Line= 6
1653584.68090472464651.5700793861653497.26605331464648.708208471
1653422.32952339464646.255457475 1653322.3097103464641.392606303
1653246.38827421464612.6584118011653158.50688831464569.244456634
#Sta/Elev= 30
       0  974.65    48.8  937.28    68.5  917.92    78.3  905.93   101.3  884.26
   115.8  876.15     121  871.87   127.6  864.26   131.7  857.66   141.2  840.15
     144  835.86   147.2  832.67   163.7  823.25   180.1  810.13   194.8   804.2
   203.1  799.09   206.4   798.3   216.2  800.49   222.8   800.2   235.9  797.61
  247.22800.1782   255.6   803.9   272.7  804.15   294.7  816.62   379.4  851.66
   383.1  853.52   390.4  860.43   415.9  871.25   430.6  878.59   441.8   882.8
#Mann= 3 ,-1,0
       0      .1       0   222.8    .045       0  247.22      .1       0
Bank Sta=222.8,247.22
XS Rating Curve= 0 ,0
Exp/Cntr(USF)=0,0
Exp/Cntr=0.3,0.1

Type RM Length L Ch R = 1 ,2101    ,297.8,299.8,299.7
XS GIS Cut Line= 6
1653534.65408467464275.5750275111653449.46921568464295.438176751
1653376.43425676 464312.466686011653279.11916268464335.896429166
1653206.39063358464355.1536085011653121.59027825464377.891423926
#Sta/Elev= 30
       0  846.57    15.5  843.82    25.6  844.37    49.2  844.02    64.6   842.3
   101.7   834.4   146.9  826.33   170.5  820.68   173.9  819.19   177.3  815.93
   187.4  801.11   190.8  796.69  193.81793.9662   197.5   792.6   200.9  792.34
  220.13 793.966   231.2  796.42   241.4  796.56   258.2  799.13   309.4  801.86
   315.9   802.9   319.3  804.21   322.7  806.22   353.3  828.69     377  846.85
   380.4  850.44   390.6  865.95   400.8  877.31   407.6  883.64   425.6  897.61
#Mann= 3 ,-1,0
       0      .1       0  193.81    .045       0  220.13      .1       0
Bank Sta=193.81,220.13
XS Rating Curve= 0 ,0
Exp/Cntr(USF)=0,0
Exp/Cntr=0.3,0.1

Type RM Length L Ch R = 1 ,1801    ,354.5,332.8,305.2
XS GIS Cut Line= 6
1653465.57745117463997.6841790831653379.81417125464015.126729503
1653306.02363643464028.5414008351653207.91687725464047.970823929
1653142.03085418464120.4631330071653068.01164526464213.235585257
#Sta/Elev= 30
       0  826.87    15.2  821.23    35.3  814.38    45.4  811.75    72.2  808.81
    82.2  806.83    95.6  805.24   105.6  803.28   118.9  801.86   142.2  797.04
   182.3  792.97   191.1  790.52  194.95 789.865   202.4  789.06   215.8  788.84
  231.88789.8647   252.6  794.28   273.2  795.23   282.1  797.54   300.7  805.96
   323.9  819.83   337.8  826.47   360.5  833.75   370.7  837.91   375.1  840.23
   389.1  850.06   424.8  873.24   445.8  884.94   470.9  899.73   479.2  904.04
#Mann= 3 ,-1,0
       0      .1       0  194.95    .045       0  231.88      .1       0
Bank Sta=194.95,231.88
XS Rating Curve= 0 ,0
Exp/Cntr(USF)=0,0
Exp/Cntr=0.3,0.1

Type RM Length L Ch R = 1 ,1468    ,247.8,268.1,278.8
XS GIS Cut Line= 2
1652998.01079664463786.2884514071652991.15717285464208.847319316
#Sta/Elev= 30
       0  860.92    53.1  837.31    72.8  831.99    95.7  828.48   108.8  824.02
   115.4  820.67   139.5  805.67   151.5  799.68   167.2  789.32   171.8  787.29
   177.8  785.62   187.6  785.34200.2744783.6232   207.3  784.04   213.8  783.21
   226.4783.5935   263.1   786.4   279.5  792.83     286  796.29   302.4  807.88
   318.8  822.84   325.4  827.99   348.4  839.74   351.7  843.56   361.5  862.44
   367.3  869.06   374.6  875.25   387.8  884.02   407.4  898.68   422.6  907.25
#Mann= 3 ,-1,0
       0      .1       0200.2744    .045       0   226.4      .1       0
Bank Sta=200.2744,226.4
XS Rating Curve= 0 ,0
Exp/Cntr(USF)=0,0
Exp/Cntr=0.3,0.1

Type RM Length L Ch R = 1 ,1200    ,308,303.4,295.1
XS GIS Cut Line= 6
1652925.87938359463764.4038057631652874.63375117463843.605090916
1652812.43013543463887.3536910861652721.43392634463928.823424429
1652655.14403267463966.9260385041652581.54247384464018.309137836
#Sta/Elev= 30
       0   842.7    22.8  832.74    40.1  826.75    89.3  808.11   100.1  804.56
   108.1  800.94   132.2  788.39   156.2  782.66   166.8  782.46   179.3  780.54
   186.5  778.81   204.7  778.59     222  777.31   229.8  777.85   231.9  778.57
   234.4  779.85   260.3  798.92   273.2  807.14   292.1  820.25   326.1  837.71
   345.1  844.55   353.1   848.1     369  858.74     373  860.73     385  865.18
     389  867.79     397  874.24     401   876.7   416.3  884.46   436.6  896.06
#Mann= 3 ,-1,0
       0      .1       0   204.7    .045       0   231.9      .1       0
Bank Sta=204.7,231.9
XS Rating Curve= 0 ,0
Exp/Cntr(USF)=0,0
Exp/Cntr=0.3,0.1

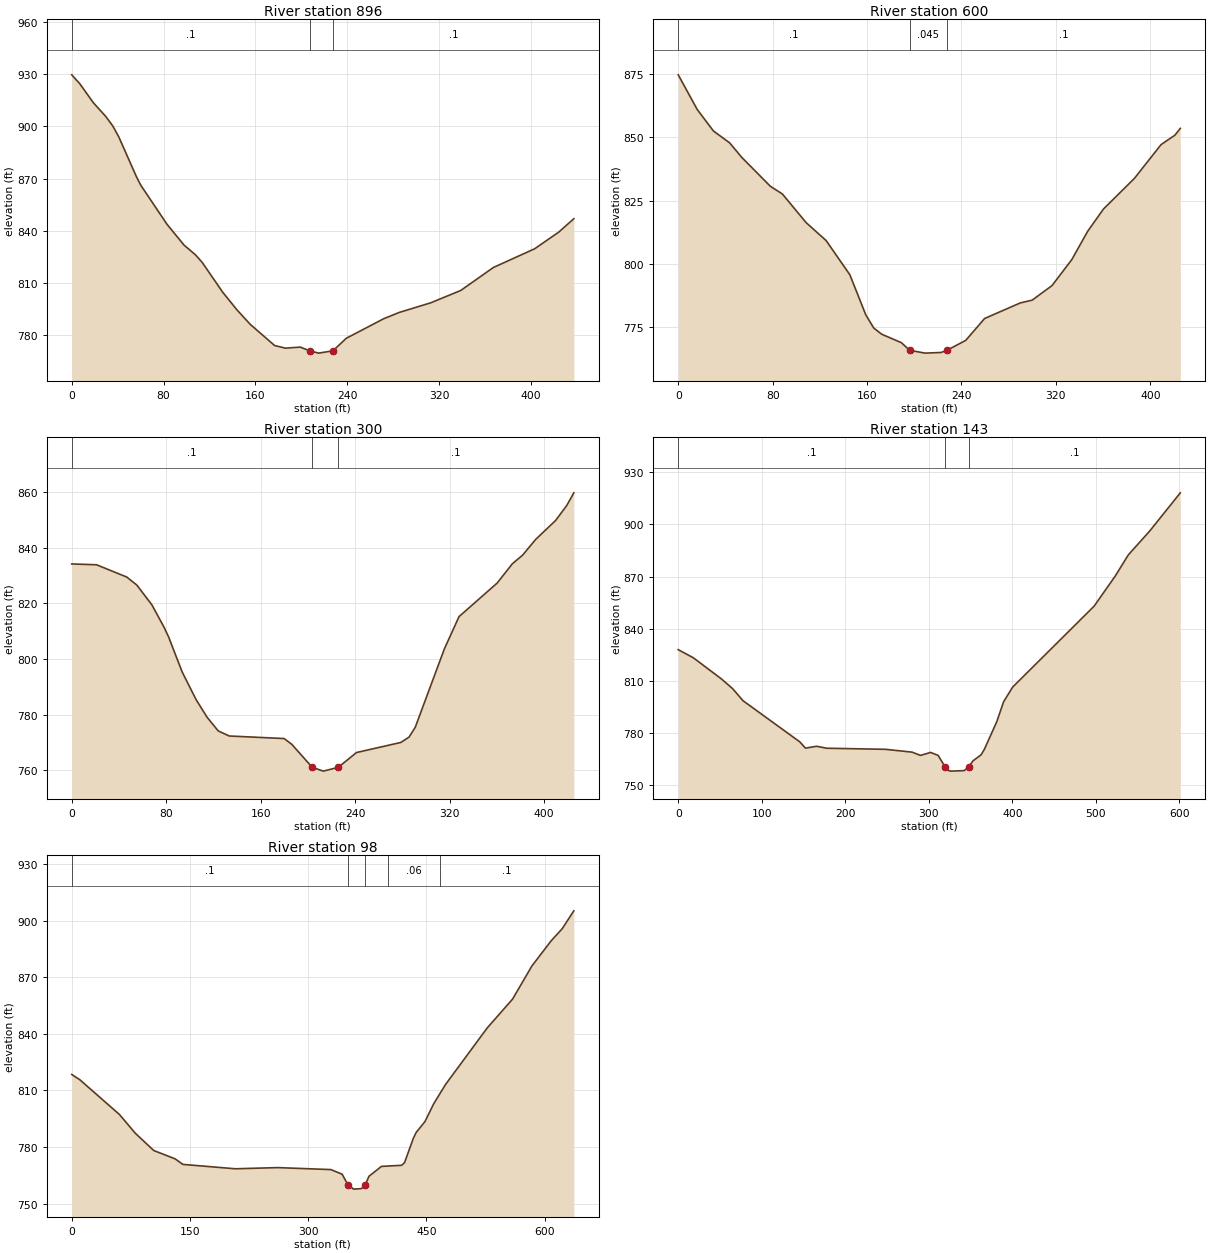
Type RM Length L Ch R = 1 ,896     ,299.4,296.5,290.3
XS GIS Cut Line= 6
1652696.57570834463492.3859770891652651.87599459463567.606627166
1652613.56176676463632.0815638451652556.39291784463714.433105171
1652502.14565101463773.2866620121652440.10148376463844.724183172
#Sta/Elev= 30
       0  929.62       7   924.5    18.9   913.5    29.6  905.71    35.7  900.26
      41   893.9    56.3  871.09    60.1  866.18      83  843.68    97.9  831.67
   107.5  826.31   113.6  821.81   131.5  804.65   144.1  794.36   155.5  786.17
   176.7  774.01   186.2  772.48   199.1   773.1  207.15  770.98   215.1  769.63
  227.59770.9819   239.1  778.15     272  789.48   285.4  793.05   312.7  798.55
   338.9  805.66   367.3  818.86   403.3  829.63   424.3  839.22   437.4  846.91
#Mann= 3 ,-1,0
       0      .1       0  207.15    .045       0  227.59      .1       0
Bank Sta=207.15,227.59
XS Rating Curve= 0 ,0
Exp/Cntr(USF)=0,0
Exp/Cntr=0.3,0.1

Type RM Length L Ch R = 1 ,600     ,293.5,300,305.8
XS GIS Cut Line= 6
1652356.36871159463381.1142180121652329.86449951463464.896202669
1652313.76512225463538.1480246781652292.52238259463635.865676999
1652276.59032784463709.1539162551652258.00276659463794.657026082
#Sta/Elev= 30
       0  874.72    16.1  861.02    29.8  852.53    43.6  847.81    53.9  842.05
      78  830.68    88.3  827.59   108.3  816.33   125.3  809.21   145.4   795.7
   158.9  779.86   165.6  774.66   172.3   772.2   189.1  768.82  196.09765.8112
   209.2   764.7   222.7  764.96  227.65765.8098   243.6  769.74   259.6   778.4
   289.8  784.54   299.9  785.65   316.7   791.4   333.5   801.7   346.9  812.85
   360.3  821.67   386.5  833.77   409.1  847.14   420.8  850.85   425.4  853.56
#Mann= 3 ,-1,0
       0      .1       0  196.09    .045       0  227.65      .1       0
Bank Sta=196.09,227.65
XS Rating Curve= 0 ,0
Exp/Cntr(USF)=0,0
Exp/Cntr=0.3,0.1

Type RM Length L Ch R = 1 ,300     ,153.7,157.3,161.9
XS GIS Cut Line= 6
1652175.03574093463275.2499284151652119.16249309463342.698940501
1652073.80267568463402.4278236781652013.47569659463482.181601167
1651968.23070835463541.9970983421651915.44439659463611.781735674
#Sta/Elev= 30
       0  834.21      21  833.91    46.6  829.49    55.1  826.61    67.9  819.47
    78.1  811.48    81.9  808.08    93.5  795.36   105.2   785.5   114.6  779.09
     124   774.2   133.3  772.37   179.8  771.45   186.2  769.41  203.63 761.101
     213  759.74  225.63761.1022   241.1  766.43   278.6  770.04   285.6  771.98
   290.8  775.47   315.5   803.7   327.9  815.28   360.2  827.35   373.1   834.3
   381.6  837.32   392.8  843.03   409.7  849.84   419.1  855.23   425.1  859.77
#Mann= 3 ,-1,0
       0      .1       0  203.63    .045       0  225.63      .1       0
Bank Sta=203.63,225.63
XS Rating Curve= 0 ,0
Exp/Cntr(USF)=0,0
Exp/Cntr=0.3,0.1

Type RM Length L Ch R = 1 ,143     ,41.7,44.3,43.9
XS GIS Cut Line= 5
1652215.24172342463214.3377563871652041.15860637463250.354953019
1651967.62349658463312.6346888621651889.80828178463367.910829591
1651766.52748205463564.004707024
#Sta/Elev= 30
       0  827.97    18.2  823.26    51.8   811.1    65.2   805.5    77.6  798.59
   145.6  774.92   152.3  771.32   165.7  772.39   177.8  771.26   248.2  770.64
   280.1  769.01   290.1  767.13   302.2  768.85   311.2  767.15  319.71760.4328
   322.4  758.65   326.3  758.09   342.4  758.38  347.68760.4894     353  764.02
   362.6  767.45   366.6  770.66   381.4   786.5   389.6  797.97   400.4  806.41
     498     853   523.4  870.38   538.9  882.45   564.6  896.23   601.2  918.18
#Mann= 3 ,-1,0
       0      .1       0  319.71    .045       0  347.68      .1       0
Bank Sta=319.71,347.68
XS Rating Curve= 0 ,0
Exp/Cntr(USF)=0,0
Exp/Cntr=0.3,0.1

Type RM Length L Ch R = 1 ,98      ,,,
XS GIS Cut Line= 5
1652220.49423126463188.075217176 1652026.1514411 463229.34492165
1651942.86167389463289.3735827031651848.31653273463337.396511546
1651741.76565936463540.743600865
#Sta/Elev= 30
       0  818.48    10.2   815.7    60.5  797.25    80.7  787.26   104.1  778.11
     131  773.74     141  770.76   207.5  768.44   261.5  769.06   328.7  768.01
     343  765.57   350.3  759.99   357.6  757.64   367.4  757.91  372.24 759.838
   377.1  764.47   392.9   769.7   418.5  770.28   422.2   771.7   433.3  784.54
     437  787.75   448.1  793.48   459.2  802.92     474  813.05   527.1  843.19
   559.2  858.45   583.8  876.06   608.1  889.35   622.2  895.82     637  905.33
#Mann= 5 ,-1,0
       0      .1       0   350.3    .045       0  372.24      .1       0
  401.34     .06       0  467.39      .1       0
Bank Sta=350.3,372.24
XS Rating Curve= 0 ,0
Exp/Cntr(USF)=0,0
Exp/Cntr=0.3,0.1
LCMann Table=0

Chan Stop Cuts=-1
Use User Specified Reach Order=0
Composite Channel Slope=5